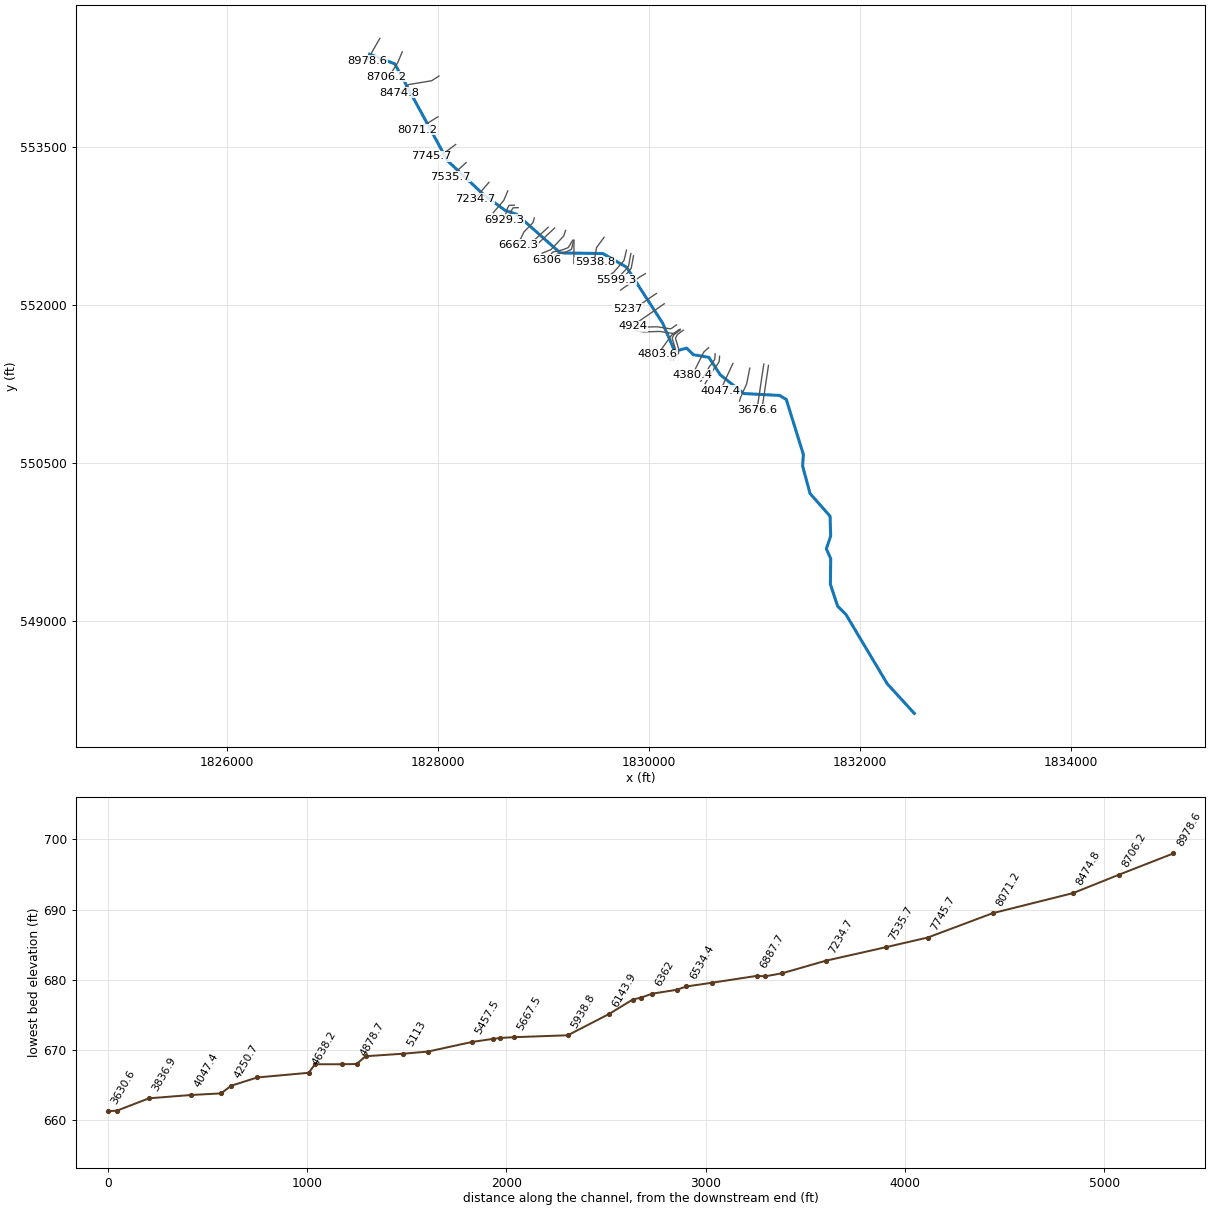
--- PATTERSNFK.prj (project) ---

Proj Title=PATTERSNFK
Current Plan=p01
Default Exp/Contr=0,0
English Units
Geom File=g01
Flow File=f01
Plan File=p01
BEGIN DESCRIPTION:
END DESCRIPTION:
DSS Export Rating Curves= 0
DSS Export Rating Curve Sorted= 0
DSS Export Volume Flow Curves= 0
DXF OffsetX= 0
DXF OffsetY= 0
DXF ScaleX= 0
DXF ScaleY= 0

--- PATTERSNFK.p01 (plan) ---

Plan Title=Floodplain
Program Version=4.00
Geom File=g01
Flow File=f01
K Sum by GR=0
Std Step Tol=0.01
Critical Tol=0.01
Num of Std Step Trials=20
Max Error Tol=0.3
Flow Tol Ratio=0.001
Split Flow NTrial=30
Split Flow Tol=0.02
Split Flow Ratio=0.02
Log Output Level=0
Friction Slope Method=1
Unsteady Friction Slope Method=2
Unsteady Bridges Friction Slope Method=1
Global Log Level=0
CheckData=False
Run HTab=0
Run UNet=0
Run PostProcess=0
UNET Theta=0
UNET Theta Warmup=0
UNET ZTol=0
UNET ZSATol=0
UNET MxIter=0
UNET MaxInSteps=0
UNET DtIC=0
UNET DtMin=0
UNET MaxCRTS=0
UNET WFStab=0
UNET SFStab=0
UNET WFX=0
UNET SFX=0
UNET DSS MLevel=0
UNET DZMax Abort=0
UNET Convert EG Bridges=0
UNET Use Existing IB Tables=0
UNET Froude Limit=0
UNET Froude Power=0
Write IC File=0
Echo Input=False
Echo Output=False
Write Detailed=0

--- PATTERSNFK.f01 (steady flow) ---

Flow Title=NFF Regression Equation
Program Version=4.10
Number of Profiles= 1
Profile Names=P100yr
River Rch & RM=PATTERSNFK,Main            ,8978.6
954.9904
River Rch & RM=PATTERSNFK,Main            ,8071.2
1063.147
River Rch & RM=PATTERSNFK,Main            ,7015.9
1092.439
River Rch & RM=PATTERSNFK,Main            ,5599.3
1170.956
River Rch & RM=PATTERSNFK,Main            ,3381.9
 1657.89
River Rch & RM=PATTERSNFK,Main            ,584.7
1730.257
Boundary for River Rch & Prof#=PATTERSNFK,Main            , 1
Up Type= 0
Dn Type= 3
Dn Slope=0.006
DSS Import GetInterval= 0
DSS Import GetPeak= 0
DSS Import FillOption= 0

--- PATTERSNFK.g01 (geometry) ---

Geom Title=USGS 10m DEM
Program Version=4.10

River Reach=PATTERSNFK      ,Main
Reach XY= 30
     1827353.759      554378.287     1827592.812      554286.091
     1828092.571      553366.076     1828432.656      553046.508
     1828635.781      552896.769      1828747.76      552857.706
     1829159.997      552491.242     1829564.166       552485.31
     1829789.426      552355.102     1830131.874       551822.55
     1830245.349      551557.265     1830358.437      551586.873
     1830422.239      551524.373     1830569.374      551499.633
     1830676.239      551334.144     1830900.104      551155.883
     1831239.947      551137.654     1831302.447      551099.894
      1831464.34      550577.694     1831457.395      550467.081
     1831527.708      550206.664     1831717.812      549990.519
      1831723.02      549803.019     1831681.981       549681.18
     1831723.373      549588.852     1831720.416      549344.685
     1831789.221      549137.088     1831867.551      549058.227
     1832259.478      548399.373     1832515.393      548118.727

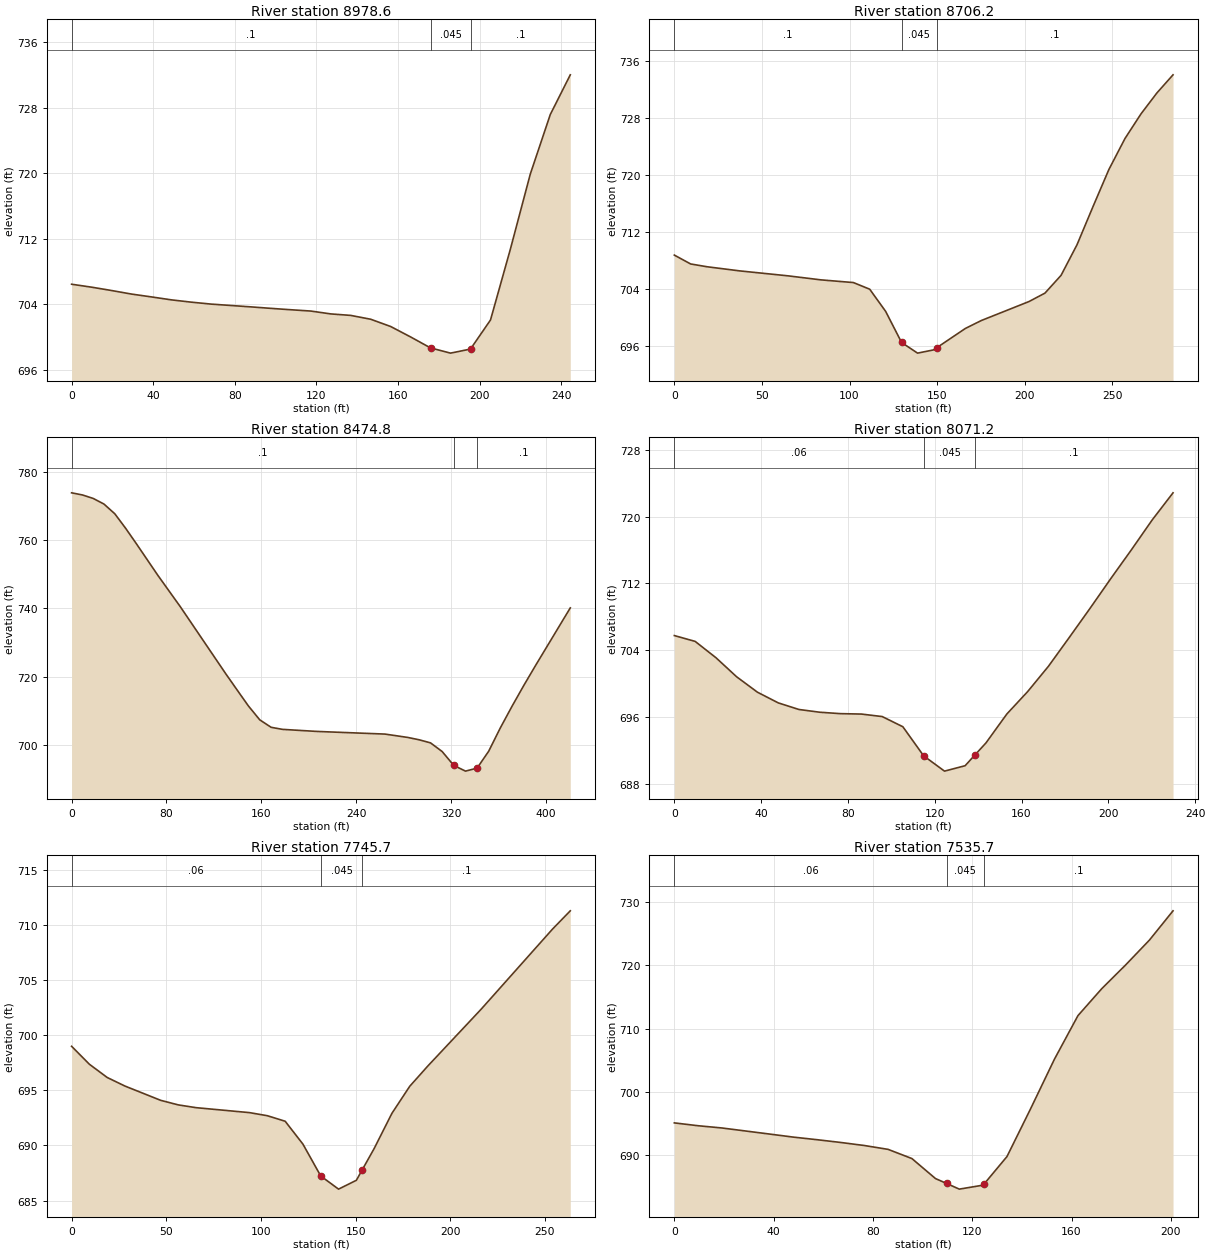
Type RM Length L Ch R = 1 ,8978.6  ,272.9,272.3,271.4
XS GIS Cut Line= 2
     1827451.024      554528.827      1827329.93      554316.588
#Sta/Elev= 28
       0  706.43     9.8  706.07    19.6  705.66    29.3  705.23    39.1  704.88
    48.9  704.52    58.6  704.24    68.4     704    78.2  703.83      88  703.66
    97.7  703.48   107.5  703.31   117.3  703.15   127.1   702.8   136.8  702.62
   146.6  702.15   156.4  701.26   166.2  699.98   173.7  698.95   175.9  698.65
   185.7  698.01   188.7  698.16   195.5  698.51   205.3  702.06     215  710.68
   224.8  719.89   234.6  727.17   244.4  732.02
#Mann= 3 , 0 , 0
       0      .1       0   175.9    .045       0   195.5      .1       0
Bank Sta=175.9,195.5
XS Rating Curve= 0 ,0
Exp/Cntr=0.3,0.1

Type RM Length L Ch R = 1 ,8706.2  ,237.7,231.5,225.4
XS GIS Cut Line= 4
     1827663.263      554399.921     1827620.294      554297.056
     1827566.909      554212.421     1827510.919      554165.546
#Sta/Elev= 25
       0  708.73     9.3  707.49    18.6   707.1    37.2  706.52      65  705.82
    83.6  705.26   102.2  704.88   111.5  703.95   120.6  700.84   129.7  696.48
   138.8  694.99   147.9  695.44   149.9  695.77   166.1  698.45   175.2  699.56
   202.4  702.22   211.5   703.4   220.7  705.89   229.8  710.18   238.9  715.51
     248  720.73   257.2  725.08   266.3  728.52   275.4  731.46   284.6     734
#Mann= 3 , 0 , 0
       0      .1       0   129.7    .045       0   149.9      .1       0
Bank Sta=129.7,149.9
XS Rating Curve= 0 ,0
Exp/Cntr=0.3,0.1

Type RM Length L Ch R = 1 ,8474.8  ,407.7,403.5,399.4
XS GIS Cut Line= 4
     1828010.919      554170.754     1827942.187      554126.106
     1827724.461      554090.025     1827637.222      554010.598
#Sta/Elev= 30
       0  773.87     9.1  773.25    18.2  772.23    27.3  770.58    36.4  767.75
    45.5  763.52    54.6  758.98    72.8  749.68    91.6  740.56   129.9  720.94
   139.5  716.18   149.1  711.46   158.7  707.38   168.3  705.19   177.9  704.59
   206.7  703.99   264.3  703.21   283.5  702.23   293.1  701.54   302.7  700.64
   312.5  698.11   322.3  694.05   332.2  692.36     342  693.24   351.8   698.2
   361.6  705.02   371.5  711.38   381.3   717.4   391.1  723.18   420.6  740.17
#Mann= 3 , 0 , 0
       0      .1       0   322.3    .045       0     342      .1       0
Bank Sta=322.3,342
XS Rating Curve= 0 ,0
Exp/Cntr=0.3,0.1

Type RM Length L Ch R = 1 ,8071.2  ,323.6,325.5,327.5
XS GIS Cut Line= 2
     1828001.805      553784.036     1827806.492      553662.942
#Sta/Elev= 27
       0  705.75     9.6  705.05    19.2  703.09    28.7  700.81    38.3  698.96
    47.9  697.68    57.4  696.89      67  696.56    76.6  696.39    86.2  696.34
    95.8  696.04   105.3  694.82   114.9  691.33   123.7  689.65   124.5   689.5
     134  690.15   138.7  691.49   143.6  692.88   153.2  696.34   162.8  699.03
   172.4  702.07   181.9  705.49   191.5  708.99   201.1  712.57   210.7  716.06
   220.2  719.61   229.8  722.86
#Mann= 3 , 0 , 0
       0     .06       0   114.9    .045       0   138.7      .1       0
Bank Sta=114.9,138.7
XS Rating Curve= 0 ,0
Exp/Cntr=0.3,0.1

Type RM Length L Ch R = 1 ,7745.7  ,207.7,210,212.1
XS GIS Cut Line= 3
     1828169.774      553521.015     1828026.544      553414.244
     1827941.909      553410.338
#Sta/Elev= 22
       0     699     9.4  697.37    18.8  696.17    28.2  695.39      47   694.1
    56.4  693.68    65.8  693.43      94  692.98   103.4   692.7   112.8   692.2
   122.2  690.12   131.6  687.23     141  686.04   150.4  686.84   153.6  687.82
   159.8  689.72   169.2  692.92   178.6  695.37   188.1   697.2   216.3  702.36
     254  709.63   263.4  711.29
#Mann= 3 , 0 , 0
       0     .06       0   131.6    .045       0   153.6      .1       0
Bank Sta=131.6,153.6
XS Rating Curve= 0 ,0
Exp/Cntr=0.3,0.1

Type RM Length L Ch R = 1 ,7535.7  ,298.2,301.1,303.9
XS GIS Cut Line= 2
     1828268.732       553349.14     1828120.294      553213.723
#Sta/Elev= 24
       0  695.12     9.6  694.67    19.1  694.32    28.7  693.84    38.3  693.36
    47.8  692.88    57.4  692.47      67  692.03    76.5  691.55    86.1  690.94
    95.7  689.49   105.2  686.33   109.7  685.55   114.8  684.66   124.4  685.29
   124.7  685.43     134   689.8   143.5  697.33   153.1  705.16   162.6  712.06
   172.2  716.32   181.8  720.06   191.4  723.99   200.9  728.61
#Mann= 3 , 0 , 0
       0     .06       0   109.7    .045       0   124.7      .1       0
Bank Sta=109.7,124.7
XS Rating Curve= 0 ,0
Exp/Cntr=0.3,0.1

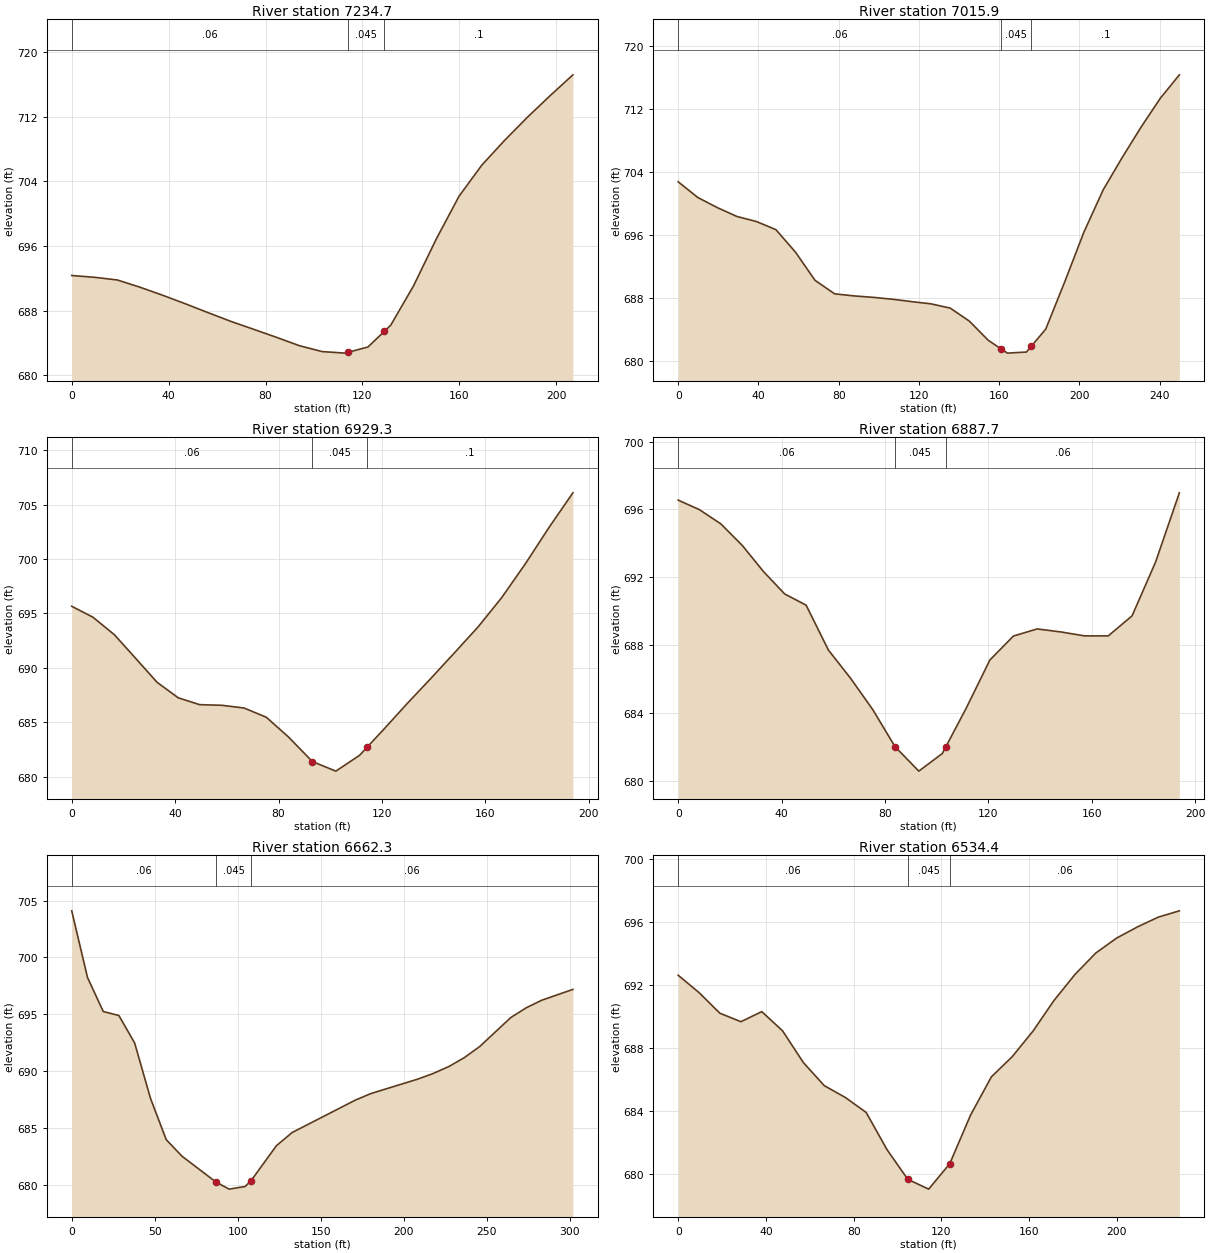
Type RM Length L Ch R = 1 ,7234.7  ,218.8,218.8,218.7
XS GIS Cut Line= 2
     1828484.878       553161.64     1828350.763      553004.088
#Sta/Elev= 25
       0  692.35     9.4  692.13    18.8   691.8    28.2   690.9    37.6   689.9
      47  688.84    56.4  687.74    65.8  686.66    75.2  685.68    84.6  684.69
      94  683.66   103.4  682.93   112.9  682.74     114  682.83   122.3   683.5
     129  685.42   131.7   686.2   141.1  691.06   150.5  696.87   159.9  702.17
   169.3  706.02   178.7  709.08   188.1  711.94   197.5  714.62   206.9   717.2
#Mann= 3 , 0 , 0
       0     .06       0     114    .045       0     129      .1       0
Bank Sta=114,129
XS Rating Curve= 0 ,0
Exp/Cntr=0.3,0.1

Type RM Length L Ch R = 1 ,7015.9  ,77.1,86.6,96.1
XS GIS Cut Line= 3
     1828663.263      553079.609     1828625.503      552989.765
     1828526.544      552873.879
#Sta/Elev= 29
       0  702.73     9.8  700.73    19.5  699.45    29.2  698.33      39  697.68
    48.7  696.65    58.5  693.78    68.2  690.21      78  688.49    87.7  688.23
    97.5  688.04     107   687.8   116.5   687.5     126  687.22   135.6  686.68
   145.1  685.03   154.6  682.58     161  681.49   164.1  680.96   173.6   681.1
     176  681.83   183.2  684.01   192.7  690.04   202.2  696.32   211.8  701.69
   221.3  705.81   230.8  709.71   240.3  713.34   249.8  716.32
#Mann= 3 , 0 , 0
       0     .06       0     161    .045       0     176      .1       0
Bank Sta=161,176
XS Rating Curve= 0 ,0
Exp/Cntr=0.3,0.1

Type RM Length L Ch R = 1 ,6929.3  ,43.9,41.6,41.7
XS GIS Cut Line= 4
     1828725.763      552944.192     1828676.284       552942.89
     1828659.357      552912.942     1828628.107      552807.473
#Sta/Elev= 25
       0  695.66     8.2  694.66    16.5  693.05    24.8  690.86      33  688.68
    41.2  687.25    49.5  686.62    58.1  686.56    66.7  686.31    75.3  685.46
    83.9  683.64    93.1  681.39    99.2   680.8   102.2  680.51   111.4  681.97
   114.2  682.69   120.6  684.32   129.7   686.7   138.9  689.02   148.1  691.39
   157.2  693.76   166.4  696.47   175.6   699.6   184.7  702.92   193.9  706.09
#Mann= 3 , 0 , 0
       0     .06       0    93.1    .045       0   114.2      .1       0
Bank Sta=93.1,114.2
XS Rating Curve= 0 ,0
Exp/Cntr=0.3,0.1

Type RM Length L Ch R = 1 ,6887.7  ,234.1,225.4,214.4
XS GIS Cut Line= 4
     1828762.222      552920.754     1828712.742      552919.452
     1828695.815      552889.504     1828664.565      552784.036
#Sta/Elev= 25
       0  696.55     8.2  695.99    16.5  695.15    24.8  693.88      33  692.34
    41.2  691.02    49.5  690.36    58.1  687.72    66.7  686.05    75.3   684.2
    83.9  682.02    88.5   681.3    93.1  680.58   102.2  681.62   103.5     682
   111.4  684.28   120.6  687.13   129.7  688.54   138.9  688.96   148.1  688.78
   157.2  688.55   166.4  688.55   175.6  689.73   184.7   692.9   193.9  696.98
#Mann= 3 , 0 , 0
       0     .06       0    83.9    .045       0   103.5     .06       0
Bank Sta=83.9,103.5
XS Rating Curve= 0 ,0
Exp/Cntr=0.3,0.1

Type RM Length L Ch R = 1 ,6662.3  ,128.9,127.8,126.7
XS GIS Cut Line= 4
     1828914.565      552823.098     1828901.544      552777.525
     1828815.607      552688.984     1828759.617      552570.494
#Sta/Elev= 25
       0  704.11     9.5  698.24      19  695.24    28.4  694.89    37.9  692.47
    47.4  687.61    56.9  683.96    66.4   682.5      87  680.21    94.8   679.6
   104.4  679.83  107.88  680.32   123.3  683.43   132.8  684.59   170.8  687.44
   180.2  688.02   208.2  689.28   217.6  689.78     227  690.39   236.3  691.17
   245.7  692.16   264.4  694.71   273.8  695.58   283.1  696.24   301.8  697.19
#Mann= 3 , 0 , 0
       0     .06       0      87    .045       0  107.88     .06       0
Bank Sta=87,107.88
XS Rating Curve= 0 ,0
Exp/Cntr=0.3,0.1

Type RM Length L Ch R = 1 ,6534.4  ,48,48,47.9
XS GIS Cut Line= 2
     1829045.642      552734.991     1828878.975      552578.741
#Sta/Elev= 27
       0  692.65     9.5  691.55      19  690.24    28.6   689.7    38.1  690.34
    47.6  689.12    57.1   687.1    66.6  685.64    76.2  684.89    85.7  683.94
    95.2  681.58   104.7  679.69   106.7  679.56   114.2  679.07   121.7  680.33
   123.8  680.68   133.3  683.77   142.8   686.2   152.3  687.48   161.8  689.11
   171.3  691.04   180.9   692.7   190.4  694.06   199.9  695.01   209.4  695.72
   218.9  696.34   228.5  696.74
#Mann= 3 , 0 , 0
       0     .06       0   104.7    .045       0   123.8     .06       0
Bank Sta=104.7,123.8
XS Rating Curve= 0 ,0
Exp/Cntr=0.3,0.1

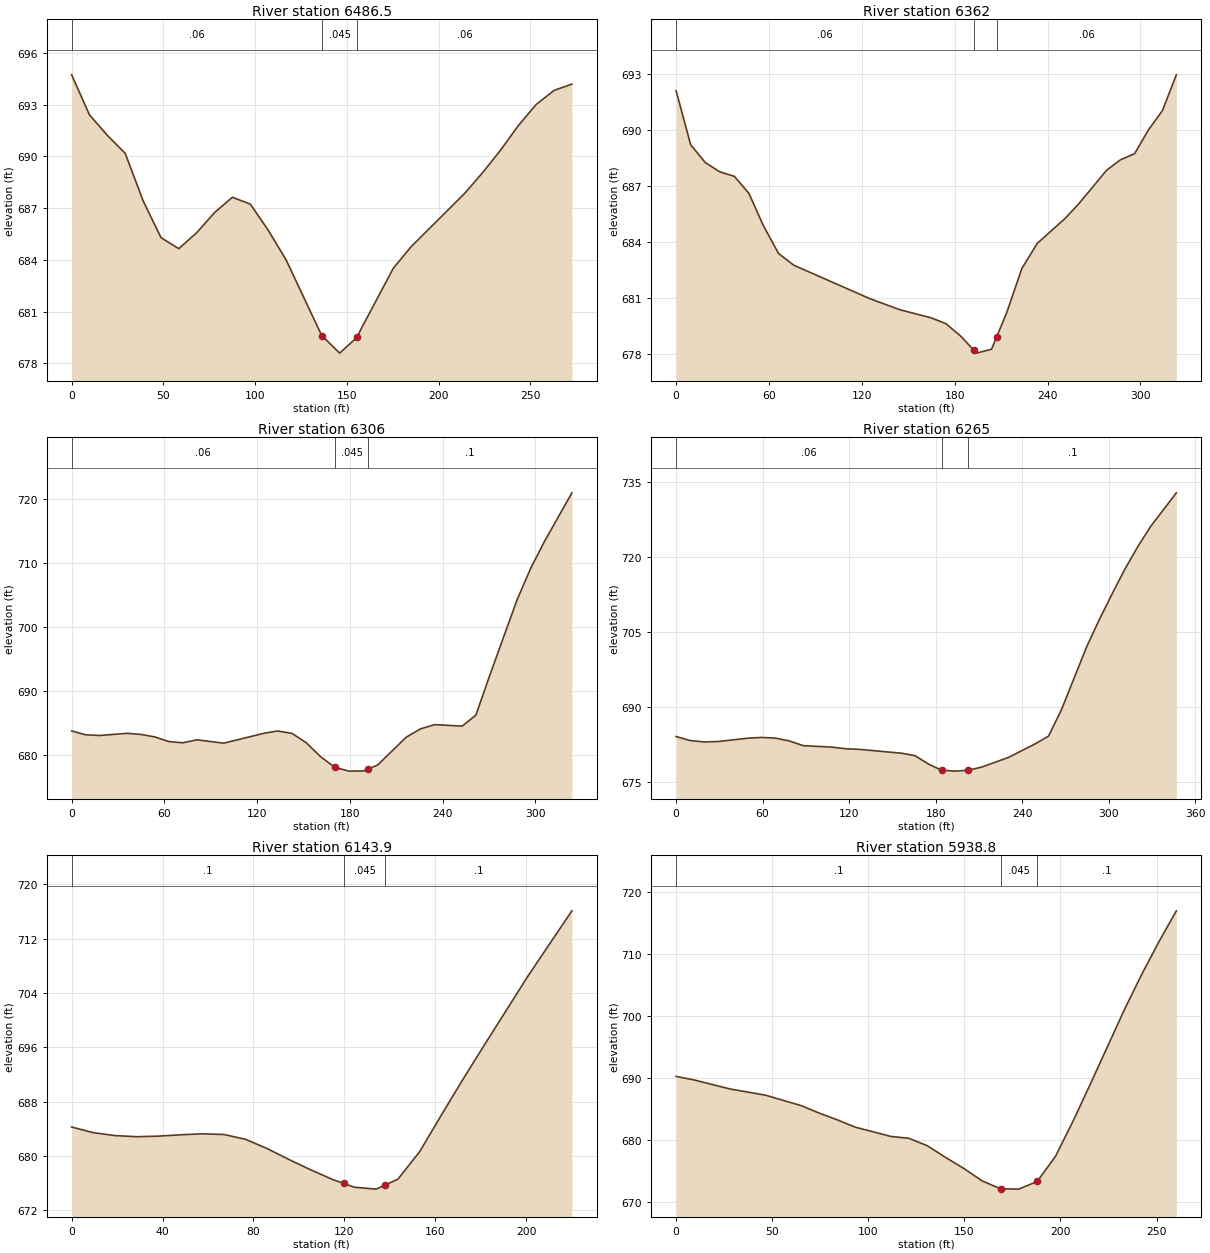
Type RM Length L Ch R = 1 ,6486.5  ,123,124.5,125.9
XS GIS Cut Line= 2
     1829107.274      552727.178     1828908.055       552540.98
#Sta/Elev= 26
       0  694.72     9.7   692.4    19.5  691.21    29.2  690.17      39  687.41
    48.7  685.29    58.4  684.65    68.2  685.58    77.9  686.74    87.6  687.63
    97.4  687.23   107.1  685.73   116.9     684   136.3  679.62   146.1   678.6
   155.8  679.54  157.31  679.91   175.3  683.51     185  684.76   214.2  687.85
     224  689.05   233.7  690.34   243.5  691.78   253.2     693     263  693.82
   272.7  694.18
#Mann= 3 , 0 , 0
       0     .06       0   136.3    .045       0   155.8     .06       0
Bank Sta=136.3,155.8
XS Rating Curve= 0 ,0
Exp/Cntr=0.3,0.1

Type RM Length L Ch R = 1 ,6362    ,70.9,55.9,39.9
XS GIS Cut Line= 4
      1829211.44      552704.609     1829193.211      552651.223
     1829072.117      552522.317     1828988.784      552488.463
#Sta/Elev= 29
       0  692.11     9.4  689.21    18.8  688.26    28.2  687.76    37.6  687.52
      47  686.61    56.4  684.87    66.2  683.38    76.1  682.75   125.2  680.96
   144.8  680.36   164.5  679.94   174.3  679.62   184.2  678.93   192.2   678.2
     194  678.04   203.8  678.25   207.2  678.93   213.6  680.21   223.4  682.58
   233.3  683.92   251.3  685.26   260.3  686.06   278.2  687.85   287.2  688.41
   296.2  688.73   305.2  690.01   314.2  691.04   323.2  692.96
#Mann= 3 , 0 , 0
       0     .06       0   192.2    .045       0   207.2     .06       0
Bank Sta=192.2,207.2
XS Rating Curve= 0 ,0
Exp/Cntr=0.3,0.1

Type RM Length L Ch R = 1 ,6306    ,56.1,41,37.7
XS GIS Cut Line= 5
     1829277.966      552611.141     1829236.299      552541.696
     1829187.688      552522.599      1829088.73      552499.162
     1829035.778      552427.981
#Sta/Elev= 30
       0  683.76       9  683.16      18  683.05      36  683.39      45  683.21
      54  682.81      63  682.09      72  681.91      81  682.37    98.4  681.85
   124.5   683.4   133.2  683.75   142.5  683.38   151.7  681.93     161  679.74
   170.2  678.08   179.4  677.48   188.7   677.5   191.9  677.82   197.9  678.43
   216.4  682.78   225.7  684.09   234.9  684.75   252.6  684.51   261.5  686.24
   270.4  692.41   288.1  704.24     297  709.21   305.9   713.4   323.6  720.97
#Mann= 3 , 0 , 0
       0     .06       0   170.2    .045       0   191.9      .1       0
Bank Sta=170.2,191.9
XS Rating Curve= 0 ,0
Exp/Cntr=0.3,0.1

Type RM Length L Ch R = 1 ,6265    ,74.1,121.1,157.6
XS GIS Cut Line= 5
     1829286.646      552611.141     1829266.681      552525.203
     1829205.049      552495.689     1829106.091      552472.252
      1829053.14      552401.071
#Sta/Elev= 30
       0  684.12     9.8  683.32    19.6  683.04    29.4  683.13      49  683.77
    58.8  683.94    68.6  683.82    78.4  683.25    88.2   682.3   107.8  682.01
   117.5  681.68   127.3  681.56   156.6  680.78   165.8  680.29     175  678.63
   184.1  677.39   193.5  677.21   202.8  677.39     212  678.02   230.5  679.94
     249  682.65   258.3  684.19   267.1  689.35   284.9  702.13   293.7  707.56
   302.6  712.71   311.5  717.67   320.4  722.13   329.2   726.1     347  732.81
#Mann= 3 , 0 , 0
       0     .06       0   184.1    .045       0   202.8      .1       0
Bank Sta=184.1,202.8
XS Rating Curve= 0 ,0
Exp/Cntr=0.3,0.1

Type RM Length L Ch R = 1 ,6143.9  ,208.9,205.1,201.6
XS GIS Cut Line= 2
     1829290.867      552610.859     1829289.565      552390.806
#Sta/Elev= 27
       0  684.27     9.6  683.43    19.1  683.01    28.7  682.84    38.3  682.93
    47.8  683.12    57.4  683.27      67  683.17    76.5  682.46    86.1  681.08
    95.7  679.47   105.2  677.96   114.8  676.54   119.7  675.96   124.4   675.4
     134  675.12   134.7  675.23  137.95  675.74   143.5  676.57   153.1  680.63
   162.6     686   172.2  691.32   181.8  696.47   191.4  701.55   200.9  706.58
   210.5  711.35   220.1  716.12
#Mann= 3 , 0 , 0
       0      .1       0   119.7    .045       0  137.95      .1       0
Bank Sta=119.7,137.95
XS Rating Curve= 0 ,0
Exp/Cntr=0.3,0.1

Type RM Length L Ch R = 1 ,5938.8  ,283.5,271.3,258.6
XS GIS Cut Line= 4
     1829576.024      552639.504     1829504.409      552541.848
     1829490.086      552457.213     1829488.784      552403.827
#Sta/Elev= 24
       0  690.31     9.3  689.74      28  688.28    46.6  687.27    65.2  685.58
    74.5  684.38    83.8  683.31    93.2  682.12   111.8  680.62   121.1  680.32
   130.6  679.14   140.2  677.24   149.7  675.46   159.2  673.46   168.8  672.17
   178.3  672.12   187.9  673.36   197.4   677.4   206.9  683.32   215.8  689.24
   233.6   701.3   242.5   706.9   251.4  712.13   260.3  717.02
#Mann= 3 , 0 , 0
       0      .1       0   168.8    .045       0   187.9      .1       0
Bank Sta=168.8,187.9
XS Rating Curve= 0 ,0
Exp/Cntr=0.3,0.1

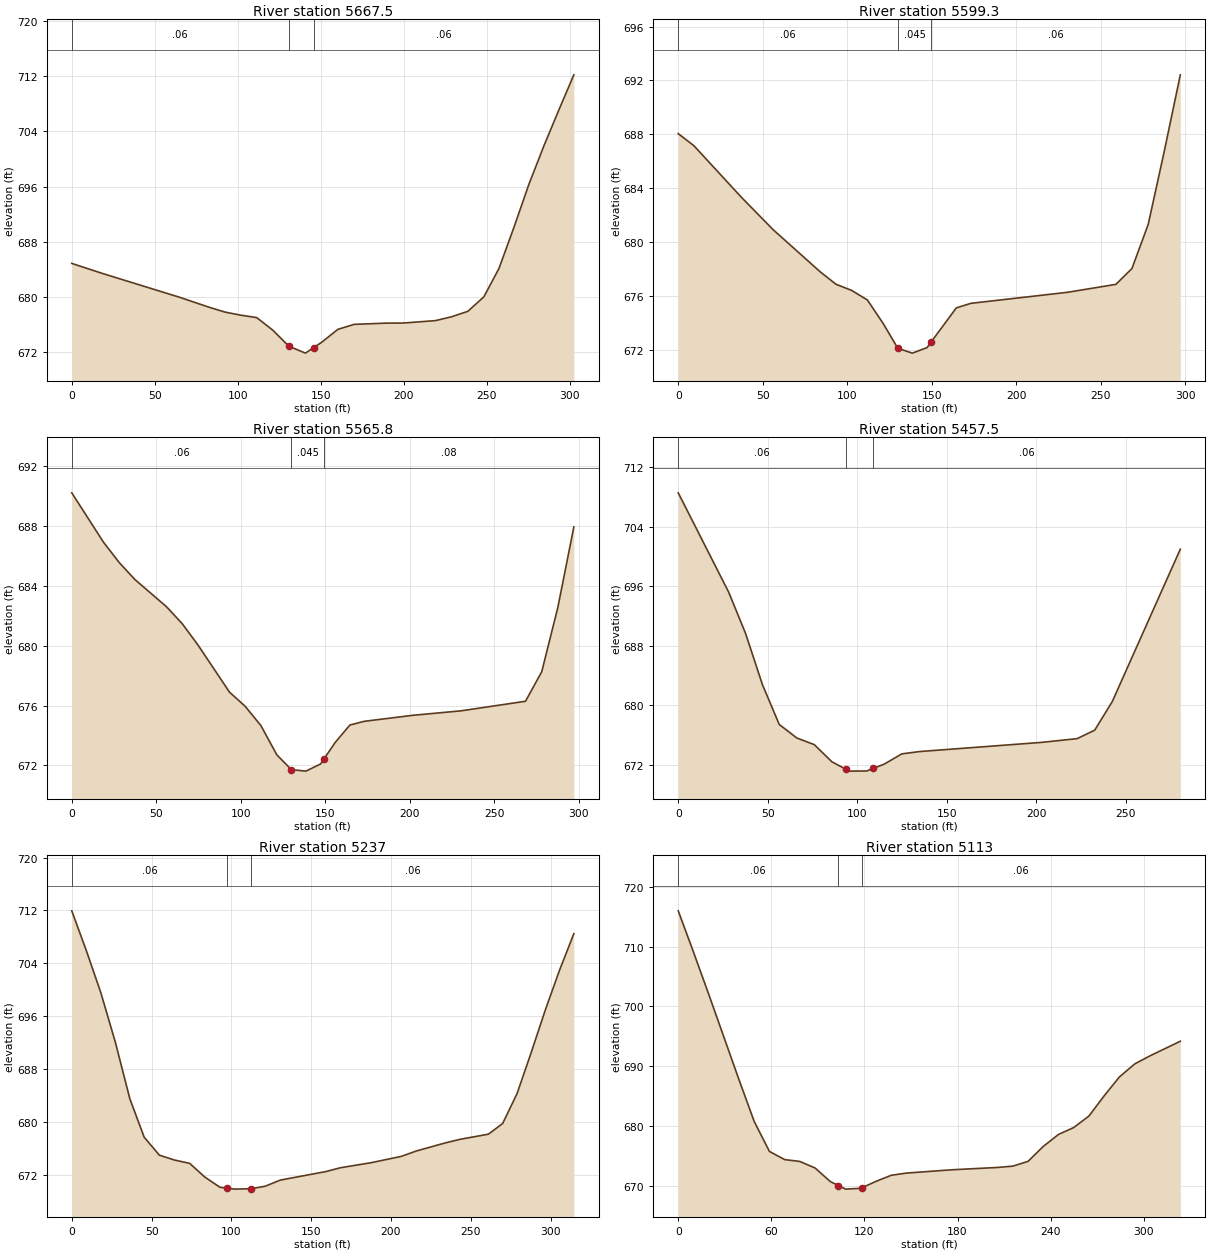
Type RM Length L Ch R = 1 ,5667.5  ,66.5,68.2,69
XS GIS Cut Line= 4
     1829788.263      552518.411     1829764.826      552419.452
     1829668.472      552308.775     1829624.201      552277.525
#Sta/Elev= 26
       0  684.86    18.5   683.4    64.7  679.97    83.2  678.47    92.4   677.8
   101.7  677.36   111.5     677   121.3  675.15   130.8  672.86   140.8  671.85
   145.8  672.65   150.6  673.42   160.4   675.3   170.2  676.02   189.7   676.2
   199.5  676.21   219.1  676.56   228.9  677.12   238.7  677.91   248.4  680.02
   257.5  684.14   266.5  690.09   275.5  696.32   284.6  701.93   293.6  707.12
   302.6   712.2
#Mann= 3 , 0 , 0
       0     .06       0   130.8    .045       0   145.8     .06       0
Bank Sta=130.8,145.8
XS Rating Curve= 0 ,0
Exp/Cntr=0.3,0.1

Type RM Length L Ch R = 1 ,5599.3  ,33.1,33.4,33.4
XS GIS Cut Line= 4
      1829829.93      552485.859     1829808.055      552366.588
     1829775.416       552326.31     1829689.305      552237.161
#Sta/Elev= 21
       0  688.05     9.3  687.15    37.3  683.33      56  680.93      84  677.78
    93.3  676.86   102.6   676.4   111.9  675.69   121.3  673.93   129.9   672.1
   138.5  671.74   147.2  672.15   149.6  672.57   164.5   675.1   173.1  675.44
   230.3  676.26   258.9  676.85   268.4  678.03     278   681.3   287.5  686.73
     297  692.42
#Mann= 3 , 0 , 0
       0     .06       0   129.9    .045       0   149.6     .06       0
Bank Sta=129.9,149.6
XS Rating Curve= 0 ,0
Exp/Cntr=0.3,0.1

Type RM Length L Ch R = 1 ,5565.8  ,116.3,108.3,101.8
XS GIS Cut Line= 4
      1829854.93      552463.636     1829833.055      552344.366
     1829800.416      552304.088     1829714.305      552214.938
#Sta/Elev= 24
       0  690.22    18.7  686.93      28  685.57    37.3  684.43      56  682.61
    65.3  681.48    74.6  680.06    93.3   676.9   102.6  675.95   111.9  674.66
   121.3  672.71   129.9  671.72   138.5  671.62   147.2   672.1   149.1  672.42
   155.8  673.53   164.5   674.7   173.1  674.95   201.7  675.35   230.3  675.65
   268.4  676.29     278  678.26   287.5  682.54     297  687.94
#Mann= 3 , 0 , 0
       0     .06       0   129.9    .045       0   149.1     .08       0
Bank Sta=129.9,149.1
XS Rating Curve= 0 ,0
Exp/Cntr=0.3,0.1

Type RM Length L Ch R = 1 ,5457.5  ,220.1,220.6,220.7
XS GIS Cut Line= 4
     1829966.909      552293.584     1829918.081      552265.372
     1829764.001      552161.206     1829733.619      552138.419
#Sta/Elev= 20
       0  708.59    28.2  695.22    37.6  689.69      47  682.82    56.4  677.45
    66.2  675.63      76  674.73    85.8  672.43    93.9  671.39    95.6  671.17
   105.3  671.19   108.9  671.53   115.1  672.12   124.9  673.49   134.7   673.8
   203.2  675.04   222.8  675.54   232.6  676.68   242.4  680.52   280.4  701.01
#Mann= 3 , 0 , 0
       0     .06       0    93.9    .045       0   108.9     .06       0
Bank Sta=93.9,108.9
XS Rating Curve= 0 ,0
Exp/Cntr=0.3,0.1

Type RM Length L Ch R = 1 ,5237    ,124,123.9,123.9
XS GIS Cut Line= 4
     1830072.161      552105.867     1830034.183      552080.911
     1829886.614      551977.829     1829798.723      551962.638
#Sta/Elev= 30
       0  711.93     9.1  705.93    18.2  699.55    27.3  692.05    36.4  683.47
    45.4  677.65    54.9  674.94    64.4   674.2    73.9   673.7    83.3  671.64
    92.8  670.09    97.5  669.95   102.3   669.8   112.5  669.87   121.2  670.24
   130.7  671.17   159.1  672.45   168.6  673.05   187.6   673.8   206.5  674.76
     216  675.58   234.4  676.82   243.3  677.34   261.1  678.12     270  679.74
     279  684.25   287.9  690.49   296.8  696.97   305.7  702.98   314.6  708.47
#Mann= 3 , 0 , 0
       0     .06       0    97.5    .045       0   112.5     .06       0
Bank Sta=97.5,112.5
XS Rating Curve= 0 ,0
Exp/Cntr=0.3,0.1

Type RM Length L Ch R = 1 ,5113    ,206.8,189,170.7
XS GIS Cut Line= 2
     1830145.945      552008.211     1829880.103      551823.749
#Sta/Elev= 30
       0  715.96     9.8   709.1    19.6  702.07    39.2  687.74      49  680.78
    58.8  675.79    68.6  674.43    78.4  674.12    88.2  673.03      98  670.77
   103.2   670.1   107.9   669.5   117.7  669.64   118.2   669.7   127.5   670.8
   137.3  671.81   147.1  672.18   176.5  672.73   205.9  673.12   215.7  673.34
   225.5  674.14   235.3  676.63   245.1  678.63   254.9  679.78   264.7   681.7
   274.6   685.1   284.4  688.24   294.2   690.4     304  691.74   323.6  694.19
#Mann= 3 , 0 , 0
       0     .06       0   103.2    .045       0   118.2     .06       0
Bank Sta=103.2,118.2
XS Rating Curve= 0 ,0
Exp/Cntr=0.3,0.1

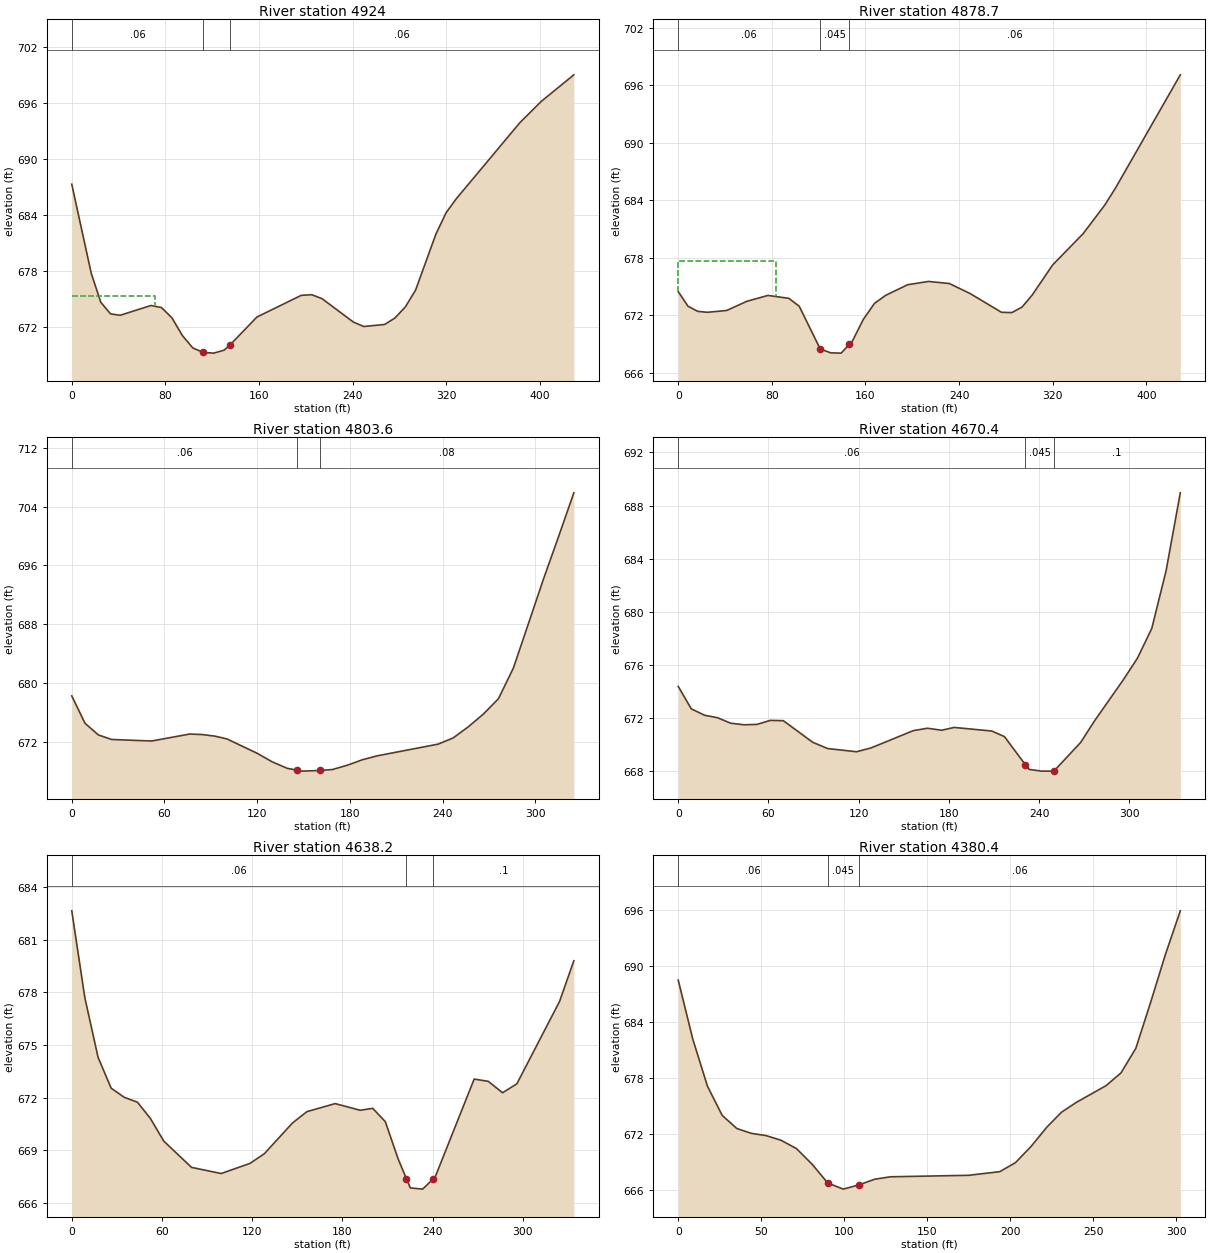
Type RM Length L Ch R = 1 ,4924    ,46.4,45.3,45.6
XS GIS Cut Line= 6
     1830260.963      551807.473     1830220.815      551778.176
     1830204.539      551770.581     1830077.586      551790.112
     1829927.847      551785.772     1829845.381      551795.537
#Sta/Elev= 30
       0  687.29    16.6  677.74    24.8  674.61    33.1  673.36    41.4  673.21
    67.7  674.26    76.6  674.04    85.5  672.95    94.5  671.03   103.4   669.7
   112.4  669.21   121.3  669.14   130.2  669.46     135  669.99   158.2  673.02
   196.1  675.35     205  675.42   213.9  674.99   240.6  672.48   249.5     672
   267.3  672.22   276.2  672.92   285.1  674.12   293.8  675.92   311.2  681.95
   319.9  684.24   328.6  685.74   382.9  693.91   401.3  696.21     429  699.05
#Mann= 3 , 0 , 0
       0     .06       0   112.4    .045       0     135     .06       0
#XS Ineff= 2 , 0
           70.86  675.27
Permanent Ineff=
       F       F
Bank Sta=112.4,135
XS Rating Curve= 0 ,0
Exp/Cntr=0.3,0.1

Type RM Length L Ch R = 1 ,4878.7  ,45.2,75.1,101.9
XS GIS Cut Line= 6
     1830287.005      551762.985     1830246.857      551733.688
     1830230.581      551726.093     1830103.628      551745.624
     1829953.888      551741.284     1829871.423       551751.05
#Sta/Elev= 30
       0  674.45     8.3  672.93    16.6  672.39    24.8  672.29    41.4  672.48
    58.7  673.44    76.6  674.05    94.5  673.75   103.4  672.92   121.3  668.47
   130.2  668.06   139.2  668.03   146.2  668.94   148.7  669.26   158.2  671.56
   167.7  673.22   177.2  674.06   196.1  675.17   213.9  675.51   231.7  675.29
   249.5  674.24   276.2  672.29   285.1  672.26   293.8  672.84   302.5   674.1
   319.9  677.23     346   680.5   364.4  683.47   373.6  685.25     429  697.07
#Mann= 3 , 0 , 0
       0     .06       0   121.3    .045       0   146.2     .06       0
#XS Ineff= 2 , 0
           83.26  677.68
Permanent Ineff=
       F       F
Bank Sta=121.3,146.2
XS Rating Curve= 0 ,0
Exp/Cntr=0.3,0.1

Type RM Length L Ch R = 1 ,4803.6  ,117.5,133.2,144
XS GIS Cut Line= 4
     1830297.627      551766.588      1830249.19       551730.65
     1830214.815      551709.817     1830084.607      551527.004
#Sta/Elev= 28
       0  678.24     8.6  674.51    17.2  672.93    25.8  672.31    51.7   672.1
    76.4  673.05    84.4  672.98    92.5  672.77   100.5  672.38     120  670.43
   129.8  669.26   139.5  668.38     146  668.13   149.3     668     161  668.09
   168.8  668.22   178.6  668.82   188.3  669.56   198.1   670.1   237.1  671.67
   246.9  672.52   256.6  674.02   266.4  675.76   276.2  677.86   285.9  682.05
   305.4  694.18   315.2  699.98     325  705.89
#Mann= 3 , 0 , 0
       0     .06       0     146    .045       0     161     .08       0
Bank Sta=146,161
XS Rating Curve= 0 ,0
Exp/Cntr=0.3,0.1

Type RM Length L Ch R = 1 ,4670.4  ,32.6,32.1,34.8
XS GIS Cut Line= 6
     1830295.685       551757.56     1830239.261      551716.327
     1830220.815      551681.605     1830251.197      551579.609
     1830250.112      551538.376     1830203.454      551478.697
#Sta/Elev= 30
       0  674.38     8.7  672.69    17.5  672.21    26.2  672.02    34.9  671.61
    43.7  671.49    52.4  671.52    61.2  671.82    69.9   671.8    89.5  670.17
    99.4   669.7   118.6  669.46   128.1  669.74   156.4  671.05   165.8  671.23
   175.2  671.08   183.6  671.29   208.6  671.02     217   670.6   230.9  668.49
   233.4  668.13   241.7     668   249.9     668   267.7  670.16   277.1  671.81
   296.1  674.88   305.5  676.51     315  678.74   324.5  683.07     334  688.96
#Mann= 3 , 0 , 0
       0     .06       0   230.9    .045       0   249.9      .1       0
Bank Sta=230.9,249.9
XS Rating Curve= 0 ,0
Exp/Cntr=0.3,0.1

Type RM Length L Ch R = 1 ,4638.2  ,272.7,257.9,246
XS GIS Cut Line= 6
     1830327.152       551757.56     1830270.728      551716.327
     1830252.282      551681.605     1830282.664      551579.609
     1830281.579      551538.376     1830234.921      551478.697
#Sta/Elev= 30
       0  682.66     8.7   677.7    17.5   674.3    26.2  672.54    34.9  672.02
    43.7  671.74    52.4   670.8    61.2  669.52    79.7  668.02    99.4  667.67
   118.6  668.25   128.1   668.8   146.9  670.56   156.4   671.2   175.2  671.66
   191.9  671.28   200.2  671.39   208.6  670.63     217  668.53  222.59  667.38
   225.2  666.85   233.4  666.78   240.3  667.35   241.7  667.46   267.7  673.06
   277.1  672.93   286.6  672.28   296.1  672.79   324.5  677.49     334  679.81
#Mann= 3 , 0 , 0
       0     .06       0  222.59    .045       0   240.3      .1       0
Bank Sta=222.59,240.3
XS Rating Curve= 0 ,0
Exp/Cntr=0.3,0.1

Type RM Length L Ch R = 1 ,4380.4  ,131.2,129.6,127.5
XS GIS Cut Line= 4
     1830566.117      551591.067     1830520.544        551549.4
     1830448.929      551406.171     1830415.075      551333.254
#Sta/Elev= 28
       0   688.5     8.8  682.16    17.6  677.14    26.5  674.01    35.3  672.61
    44.1  672.09    52.9  671.85    61.8  671.36    71.2  670.46    80.6  668.79
      90  666.78    99.4  666.12   108.9  666.58   118.3  667.18   127.7  667.44
   174.8   667.6   193.6  667.99     203  668.95   212.5   670.7   221.9  672.75
   230.8  674.36   239.8  675.42   257.6   677.2   266.6  678.57   275.5  681.19
   284.4   686.1   293.3  691.23   302.3  695.92
#Mann= 3 , 0 , 0
       0     .06       0      90    .045       0   108.9     .06       0
Bank Sta=90,108.9
XS Rating Curve= 0 ,0
Exp/Cntr=0.3,0.1

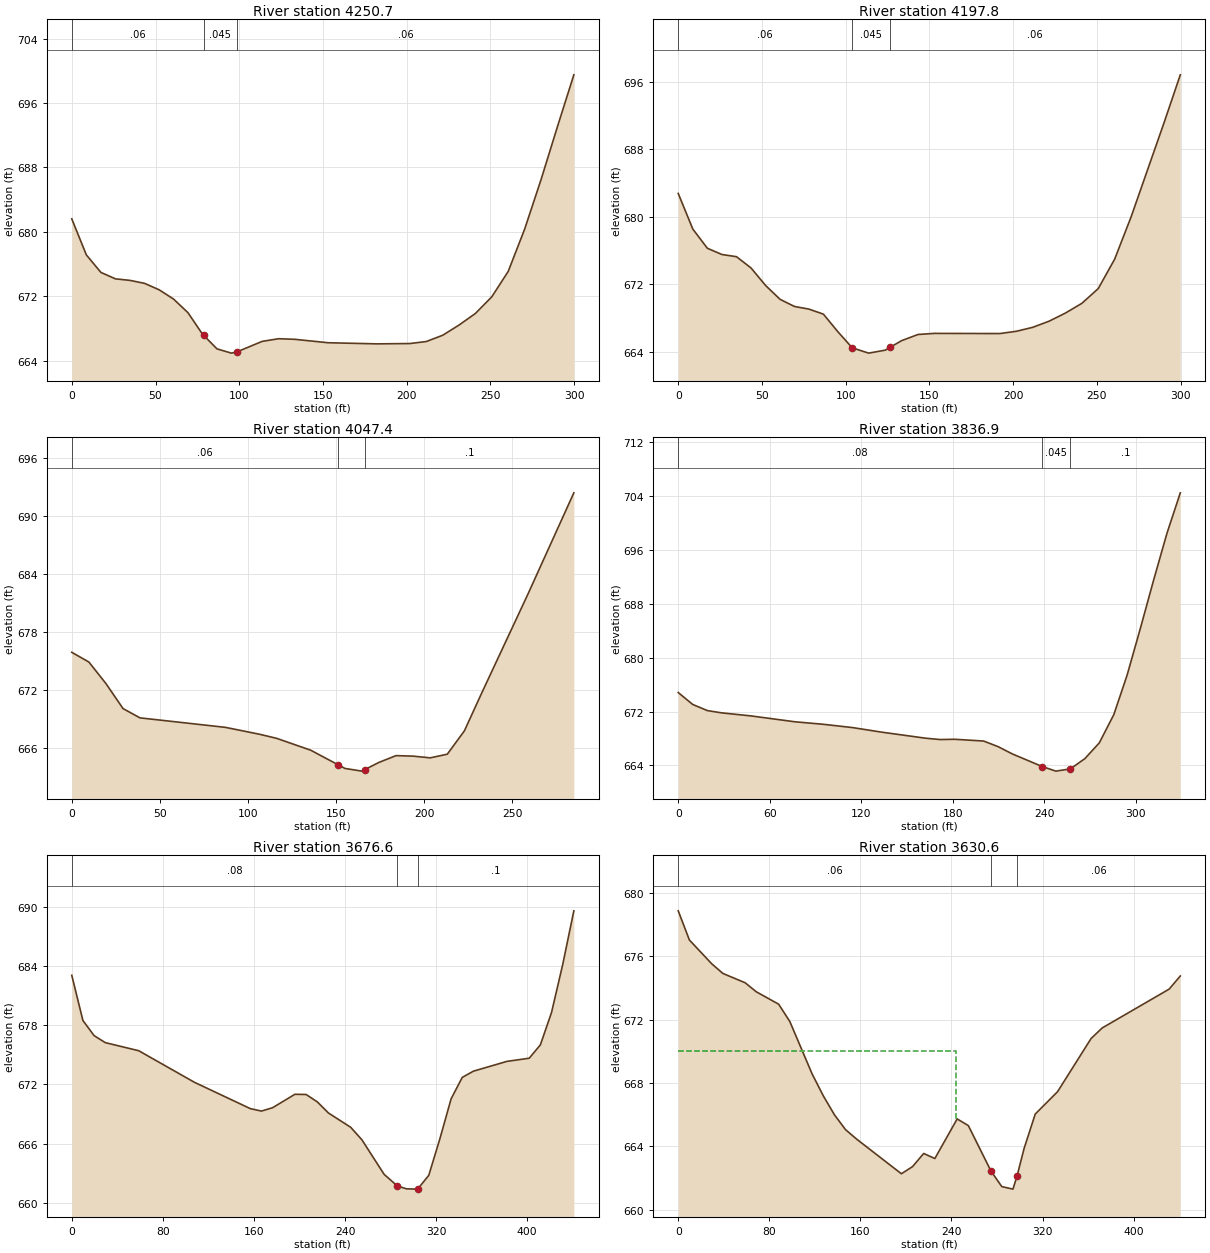
Type RM Length L Ch R = 1 ,4250.7  ,54.8,53,52.7
XS GIS Cut Line= 5
     1830628.617      551532.473     1830624.711       551480.39
     1830596.065      551437.421     1830576.534      551415.286
     1830491.898      551272.056
#Sta/Elev= 30
       0  681.62     8.7  677.15    17.4  674.97    26.1  674.17    34.8  673.98
    43.5  673.61    52.2  672.81    60.8  671.66    69.4  669.97      78  667.32
    78.7  667.17    86.7  665.48    95.3  664.95   98.58   665.1   113.7  666.41
   123.6  666.74   133.4  666.66     153  666.24   182.3   666.1   201.9  666.14
   211.7  666.39   221.5  667.17   231.2  668.43     241  669.87   250.8  671.94
   260.6  675.09   270.4  680.33   280.2  686.48     290  693.06   299.8   699.5
#Mann= 3 , 0 , 0
       0     .06       0    78.7    .045       0   98.58     .06       0
Bank Sta=78.7,98.58
XS Rating Curve= 0 ,0
Exp/Cntr=0.3,0.1

Type RM Length L Ch R = 1 ,4197.8  ,146,150.4,154.2
XS GIS Cut Line= 5
     1830670.284      551510.338     1830666.377      551458.254
     1830637.732      551415.286       1830618.2       551393.15
     1830533.565      551249.921
#Sta/Elev= 30
       0  682.78     8.7  678.56    17.4  676.28    26.1  675.54    34.8  675.28
    43.5  673.94    52.2  671.86    60.8  670.23    69.4  669.38      78  669.07
    86.7  668.47    95.3  666.39   103.9  664.48   113.7  663.85   123.6   664.2
   126.6  664.55   133.4  665.33   143.2  666.06     153  666.19   192.1  666.17
   201.9  666.44   211.7  666.91   221.5  667.64   231.2   668.6     241  669.75
   250.8   671.5   260.6  674.99   270.4  679.99     290  691.11   299.8  696.84
#Mann= 3 , 0 , 0
       0     .06       0   103.9    .045       0   126.6     .06       0
Bank Sta=103.9,126.6
XS Rating Curve= 0 ,0
Exp/Cntr=0.3,0.1

Type RM Length L Ch R = 1 ,4047.4  ,210,210.5,210.3
XS GIS Cut Line= 3
     1830796.586      551441.327     1830698.929       551230.39
     1830678.096      551182.213
#Sta/Elev= 22
       0  675.89     9.7  674.89    19.4  672.66    29.1  670.08    38.7  669.12
    87.2  668.14   106.5  667.43   116.2  667.01   135.6  665.78   151.2  664.27
     155   663.9   164.6  663.62   166.2  663.77   174.3  664.52     184  665.22
   193.7  665.17   203.4  664.99   213.1  665.37   222.8  667.78   232.4   671.6
   258.7  681.84   284.9  692.36
#Mann= 3 , 0 , 0
       0     .06       0   151.2    .045       0   166.2      .1       0
Bank Sta=151.2,166.2
XS Rating Curve= 0 ,0
Exp/Cntr=0.3,0.1

Type RM Length L Ch R = 1 ,3836.9  ,154,160.3,166.6
XS GIS Cut Line= 4
     1830956.742      551397.056     1830926.794      551247.317
     1830872.107      551126.223     1830859.086      551084.556
#Sta/Elev= 26
       0  674.82     9.5  673.05    19.1  672.14    28.6   671.8    47.7  671.35
    76.4  670.48    95.4   670.1   114.5  669.61   133.6  668.93   162.2  668.04
   171.7  667.84   181.2  667.88   200.2  667.62   209.6   666.8   219.1   665.7
   238.7  663.83   247.6  663.15   257.1  663.48   266.6     665   276.1  667.35
   285.6  671.54   294.3  677.39     303  684.34   311.8   691.6   320.5  698.51
   329.2  704.48
#Mann= 3 , 0 , 0
       0     .08       0   238.7    .045       0   257.1      .1       0
Bank Sta=238.7,257.1
XS Rating Curve= 0 ,0
Exp/Cntr=0.3,0.1

Type RM Length L Ch R = 1 ,3676.6  ,46,46,46
XS GIS Cut Line= 2
     1831089.554      551436.119      1831024.45      550999.921
#Sta/Elev= 30
       0  683.04     9.8  678.47    19.6  676.94    29.4  676.23    58.8  675.41
   107.8  672.21   156.8  669.55   166.6   669.3   176.4  669.64     196     671
   205.8  670.98   215.6  670.24   225.4  669.11     245  667.66   254.8   666.4
   274.4  662.89     286  661.72     294  661.43   303.8   661.4   313.6   662.8
   323.4  666.52   333.2  670.54     343  672.71   352.8  673.34   382.2  674.33
   401.8  674.65   411.6     676   421.4  679.28   431.2  684.12     441  689.57
#Mann= 3 , 0 , 0
       0     .08       0     286    .045       0   303.8      .1       0
Bank Sta=286,303.8
XS Rating Curve= 0 ,0
Exp/Cntr=0.3,0.1

Type RM Length L Ch R = 1 ,3630.6  ,104.3,95,84.1
XS GIS Cut Line= 2
     1831133.825      551423.098     1831068.721        550986.9
#Sta/Elev= 30
       0  678.87     9.8  677.03    29.4  675.53    39.2  674.92    58.8  674.33
    68.6  673.76    88.2  672.98      98  671.89   117.6  668.58   127.4   667.2
   137.2     666     147  665.06   156.8  664.46     196  662.28   205.8  662.73
   215.6  663.56   225.4  663.24     245  665.74   254.8  665.32   274.7  662.45
   284.2  661.47     294  661.31  297.61  662.14   303.8  663.88   313.6  666.05
   333.2  667.46   362.6  670.81   372.4  671.48   431.2  673.93     441  674.76
#Mann= 3 , 0 , 0
       0     .06       0   274.7    .045       0  297.61     .06       0
#XS Ineff= 2 , 0
          244.02     670
Permanent Ineff=
       F       F
Bank Sta=274.7,297.61
XS Rating Curve= 0 ,0
Exp/Cntr=0.3,0.1