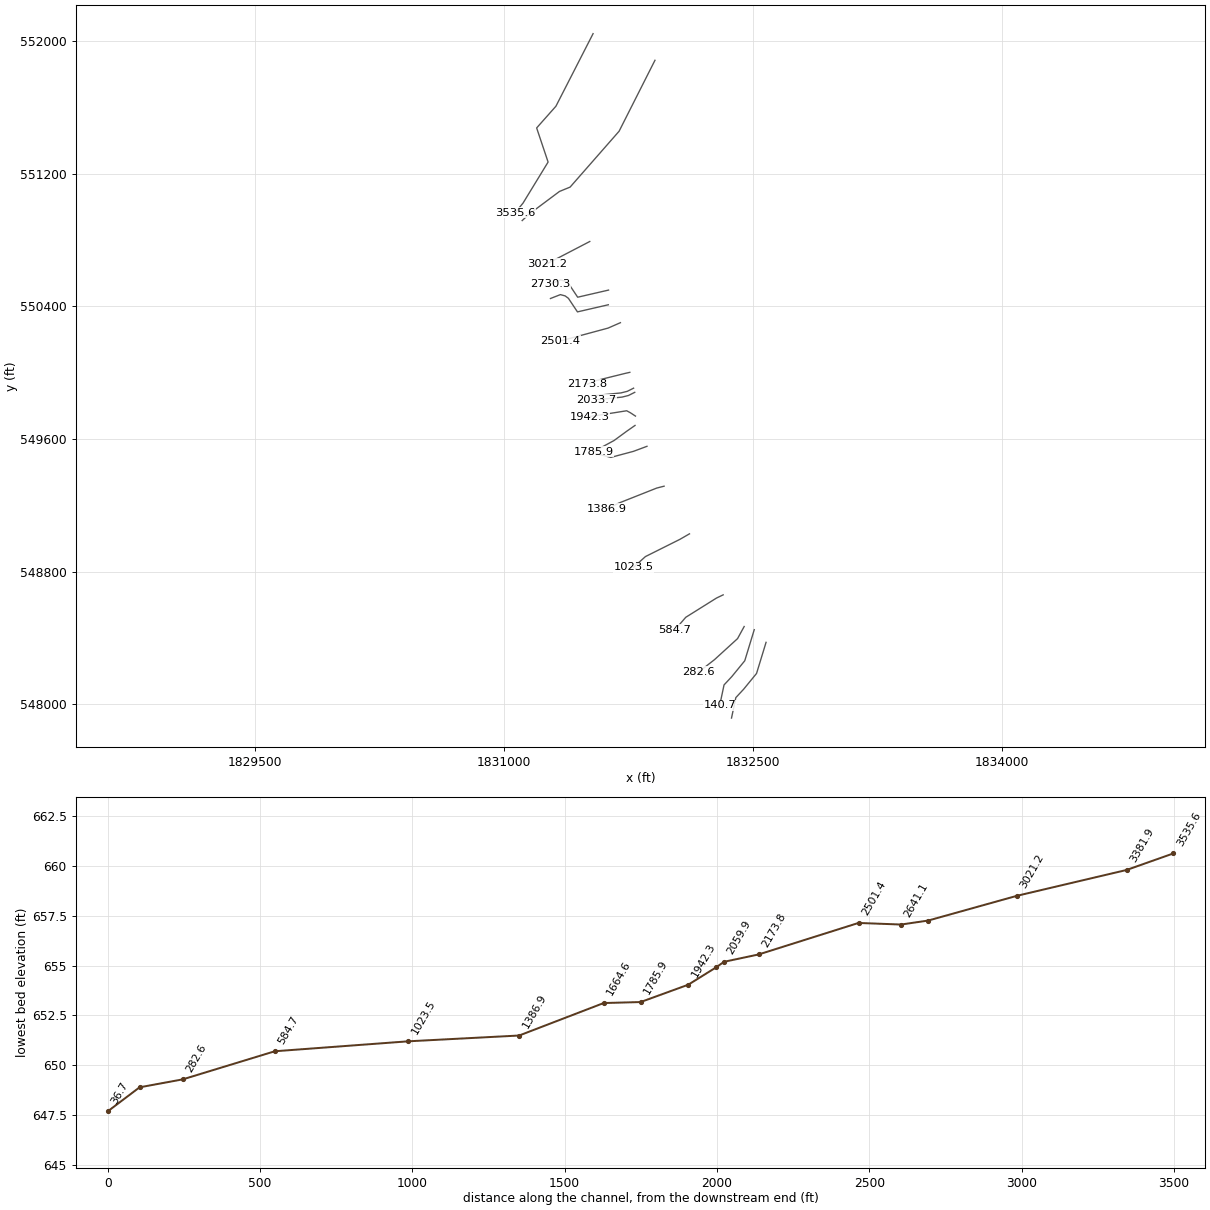
HEC-RAS study PATTERSNFK.prj: PATTERSNFK

--- PATTERSNFK.g01 (geometry) --- (continued)

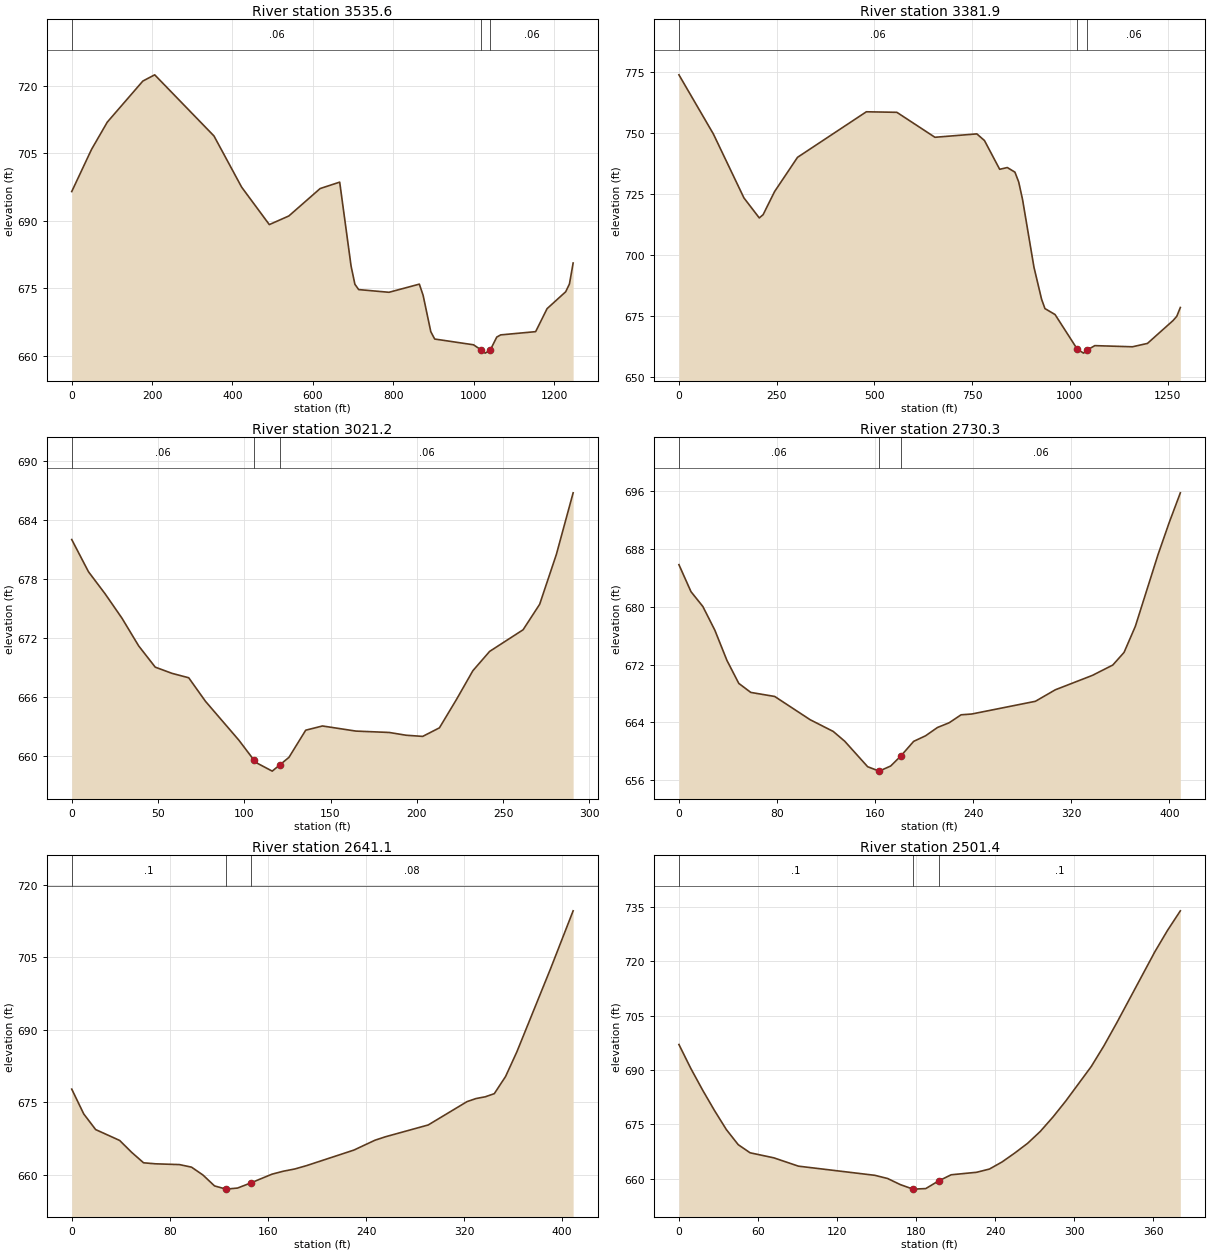
Type RM Length L Ch R = 1 ,3535.6  ,162.4,153.6,147
XS GIS Cut Line= 6
     1831536.661      552043.845     1831312.572      551606.223
     1831196.325      551475.181     1831265.336      551269.452
     1831114.294      551022.056     1831067.419      550964.765
#Sta/Elev= 30
       0  696.51    49.2  705.86    88.5  711.93     177  721.05   206.5  722.43
     354  708.85   422.8  697.49   491.7  689.17   540.3  691.09   618.2  697.18
   666.8   698.6   695.1  679.98   704.6  675.93     714  674.74   789.5  674.14
     865  675.95   874.4  673.46   893.5  665.39   903.2  663.76   999.8  662.48
  1019.1  661.33  1028.8  660.63  1041.3  661.29  1057.7   664.2  1067.4  664.68
  1154.4   665.4  1182.9  670.51  1229.2  674.26  1238.5  675.98  1247.7  680.64
#Mann= 3 , 0 , 0
       0     .06       0  1019.1    .045       0  1041.3     .06       0
Bank Sta=1019.1,1041.3
XS Rating Curve= 0 ,0
Exp/Cntr=0.3,0.1

Type RM Length L Ch R = 1 ,3381.9  ,364.6,360.8,356.4
XS GIS Cut Line= 6
     1831909.925      551883.254     1831693.604      551455.397
     1831398.148      551118.411     1831334.346      551092.369
      1831149.45      550954.348     1831109.086      550916.588
#Sta/Elev= 30
       0  773.82    88.1  749.58   166.3  723.38   205.5  715.19   215.3  716.52
   244.6  725.98   303.3  740.02   479.4  758.68   557.4  758.46   654.8  748.23
     762  749.62   781.5   746.9   820.4  735.11   839.9  735.84   859.4  733.95
   869.1  729.89   878.9  722.74   908.1  694.98   927.6  681.87   936.2  678.05
   962.1   675.6  1019.2  661.36    1035   659.8  1044.6  661.13  1063.8  662.87
    1160   662.4  1198.4  663.78  1264.1  673.18  1273.3  674.88  1282.5  678.49
#Mann= 3 , 0 , 0
       0     .06       0  1019.2    .045       0  1044.6     .06       0
Bank Sta=1019.2,1044.6
XS Rating Curve= 0 ,0
Exp/Cntr=0.3,0.1

Type RM Length L Ch R = 1 ,3021.2  ,298.3,290.9,272.3
XS GIS Cut Line= 2
     1831516.638      550790.286     1831258.825      550656.171
#Sta/Elev= 29
       0  682.04     9.7  678.77    19.4  676.51    29.1  674.05    38.8  671.23
    48.4  669.07    58.1  668.44    67.8  667.99    77.5   665.6    96.9  661.64
   105.7   659.6   106.6  659.39   116.2   658.5   120.7  659.15   125.9   659.9
   135.6  662.66   145.3  663.09   164.7  662.57     184  662.43   193.7  662.15
   203.4  662.03   213.1   662.9   222.8  665.73   232.5  668.71   242.2  670.67
   261.6  672.87   271.2  675.46   280.9  680.54   290.6  686.79
#Mann= 3 , 0 , 0
       0     .06       0   105.7    .045       0   120.7     .06       0
Bank Sta=105.7,120.7
XS Rating Curve= 0 ,0
Exp/Cntr=0.3,0.1

Type RM Length L Ch R = 1 ,2730.3  ,89.2,89.1,100.1
XS GIS Cut Line= 6
     1831629.919      550497.317     1831443.721      550454.348
     1831389.034      550536.379     1831369.502      550550.702
     1831340.857      550558.515     1831280.961      550535.077
#Sta/Elev= 30
       0  685.85     9.8  682.12    19.5  680.06    29.3  676.77    39.1  672.61
    48.8  669.41    58.6  668.16    78.1   667.6     107  664.38   125.8  662.76
   135.2   661.4   153.9  657.87   163.3  657.26   172.7  657.97   181.1  659.38
   191.4  661.38   201.1  662.15   210.8   663.3   220.4  663.96   230.1  665.06
   238.8  665.17   290.7  666.93   306.9  668.52   337.2  670.52   353.8  671.95
     363   673.7   372.2  677.31   390.6  687.19   399.8  691.68   408.9   695.8
#Mann= 3 , 0 , 0
       0     .06       0   163.3    .045       0   181.1     .06       0
Bank Sta=163.3,181.1
XS Rating Curve= 0 ,0
Exp/Cntr=0.3,0.1

Type RM Length L Ch R = 1 ,2641.1  ,137.4,139.7,142.2
XS GIS Cut Line= 6
     1831628.617      550408.775     1831442.419      550365.806
     1831387.732      550447.838       1831368.2      550462.161
     1831339.554      550469.973     1831279.659      550446.536
#Sta/Elev= 30
       0  677.73     9.8   672.6    19.5  669.37    39.1  667.12    48.8  664.68
    58.6   662.5    68.4  662.29    87.9  662.13    97.7   661.6     107  659.98
   116.4  657.73   125.8  657.06   135.2  657.28   146.2  658.36   163.3  660.15
   172.7  660.77     182  661.23   191.4  661.91   230.1  665.13   247.4  667.18
   256.1   667.9   290.7  670.32   322.4  675.15   329.8  675.79   337.2  676.14
   344.6  676.79   353.8  680.34     363  685.43   390.6  702.69   408.9  714.58
#Mann= 3 , 0 , 0
       0      .1       0   125.8    .045       0   146.2     .08       0
Bank Sta=125.8,146.2
XS Rating Curve= 0 ,0
Exp/Cntr=0.3,0.1

Type RM Length L Ch R = 1 ,2501.4  ,328.9,327.6,319
XS GIS Cut Line= 3
     1831701.534      550300.702     1831627.315       550268.15
     1831338.252      550190.025
#Sta/Elev= 30
       0  697.06       9  690.47      18  684.46      27  678.83      36  673.57
      45  669.41      54  667.17      72  665.78    90.7  663.48   148.7  660.95
   158.3  660.08     168  658.39   177.6  657.14   187.3  657.29   197.1  659.42
   206.6   661.1   225.9  661.79   235.6  662.68   245.2  664.64   254.9  667.12
   264.6  669.79   274.2  673.06   283.9  677.07   293.6  681.49   312.9  690.99
   322.5   696.7   332.2  703.02   361.2   722.7   370.8  728.59   380.5  733.97
#Mann= 3 , 0 , 0
       0      .1       0   177.6    .045       0   197.1      .1       0
Bank Sta=177.6,197.1
XS Rating Curve= 0 ,0
Exp/Cntr=0.3,0.1

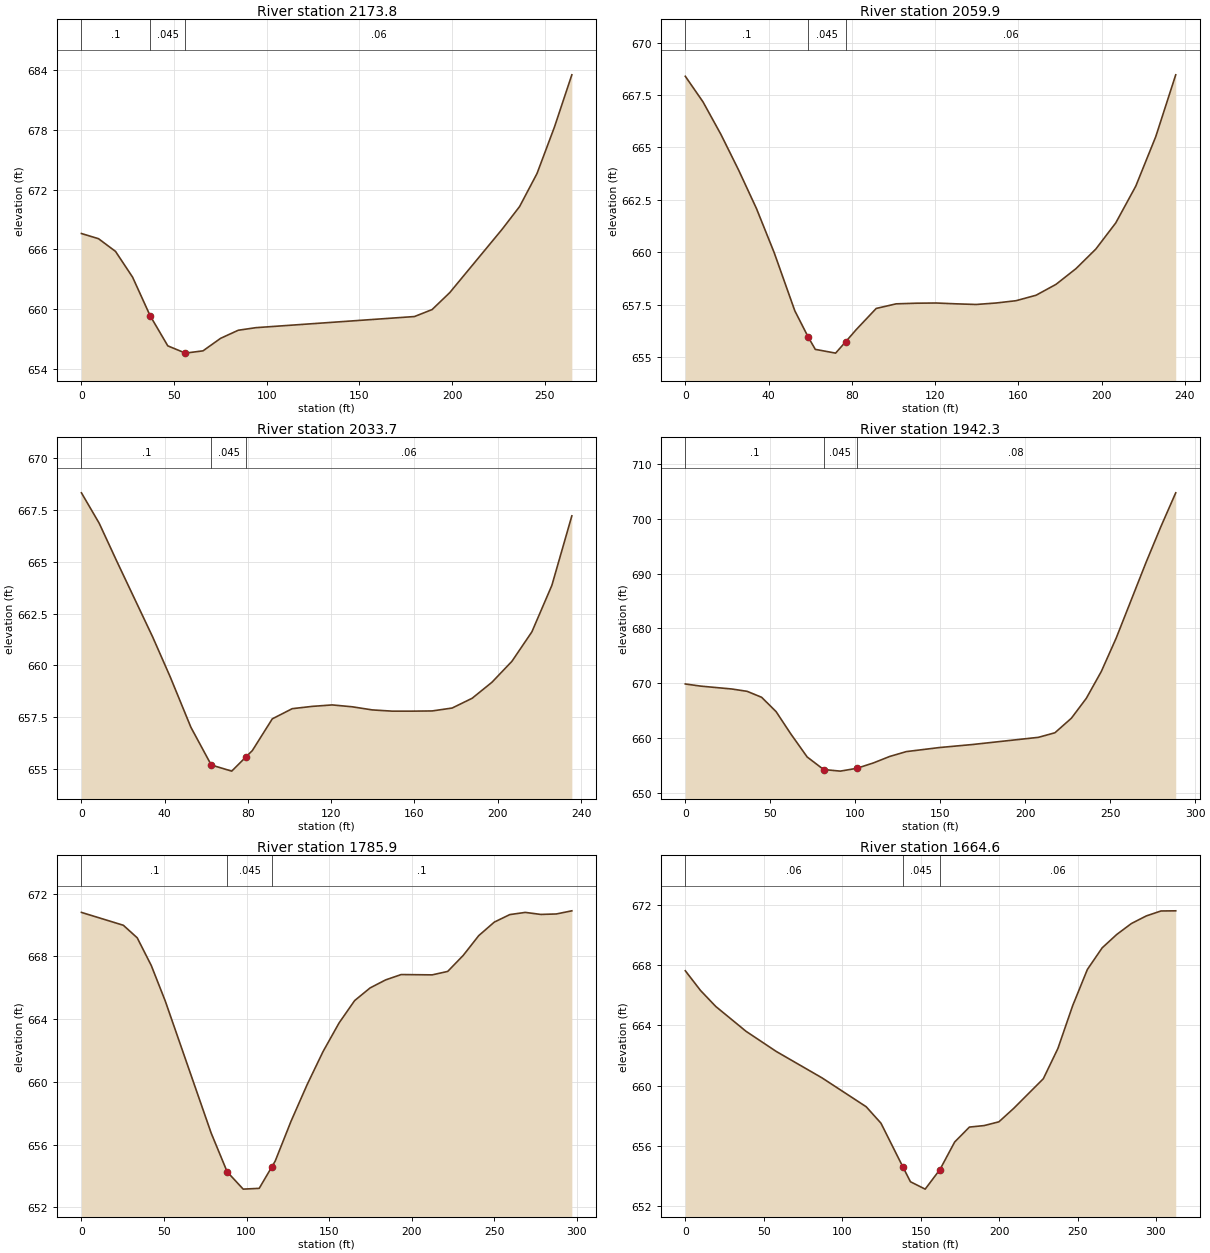
Type RM Length L Ch R = 1 ,2173.8  ,113.2,113.9,119.5
XS GIS Cut Line= 4
     1831758.391      550001.223     1831731.482      549995.147
     1831556.134      549951.744     1831504.051      549930.043
#Sta/Elev= 19
       0  667.59     9.2  667.07    18.4  665.79    27.6   663.2    37.1  659.31
    46.6  656.29    56.1  655.56    65.6  655.79    75.1  657.05    84.6  657.86
    94.1  658.12   179.7  659.24   189.2  659.94   198.7  661.64     227  668.02
   236.4   670.3   245.8  673.62   255.2  678.29   264.6  683.55
#Mann= 3 , 0 , 0
       0      .1       0    37.1    .045       0    56.1     .06       0
Bank Sta=37.1,56.1
XS Rating Curve= 0 ,0
Exp/Cntr=0.3,0.1

Type RM Length L Ch R = 1 ,2059.9  ,26.2,26.1,25.8
XS GIS Cut Line= 4
     1831780.961      549905.737     1831742.766       549886.64
     1831704.572      549877.091     1831551.794      549861.466
#Sta/Elev= 29
       0  668.39     8.5  667.17    17.1  665.62    25.6  663.92    34.2  662.08
    42.7  659.98    52.6  657.21   59.12  655.94    62.1  655.43    62.4  655.37
    72.2  655.19    77.1  655.74    82.1  656.31    91.7  657.32   101.3  657.54
   110.9  657.57   120.5  657.58   130.1  657.54   139.7  657.51   149.3  657.58
   158.9  657.69   168.5  657.95   178.1  658.47   187.7  659.22   197.2  660.15
   206.8   661.4   216.4  663.15     226  665.51   235.6  668.46
#Mann= 3 , 0 , 0
       0      .1       0   59.12    .045       0    77.1     .06       0
Bank Sta=59.12,77.1
XS Rating Curve= 0 ,0
Exp/Cntr=0.3,0.1

Type RM Length L Ch R = 1 ,2033.7  ,92.7,91.4,92
XS GIS Cut Line= 4
     1831787.905      549880.563     1831749.711      549861.466
     1831711.516      549851.918     1831558.738      549836.293
#Sta/Elev= 28
       0  668.32     8.5  666.86    17.1     665    25.6   663.2    34.2  661.38
    42.7  659.44    52.6  657.02    62.4   655.2    63.9  655.16    72.2  654.91
    78.9  655.58    82.1   655.9    91.7  657.43   101.3  657.92   110.9  658.03
   120.5   658.1   130.1  658.01   139.7  657.86   149.3   657.8   158.9   657.8
   168.5  657.81   178.1  657.95   187.7  658.42   197.2  659.19   206.8   660.2
   216.4  661.62     226  663.86   235.6  667.21
#Mann= 3 , 0 , 0
       0      .1       0    62.4    .045       0    78.9     .06       0
Bank Sta=62.4,78.9
XS Rating Curve= 0 ,0
Exp/Cntr=0.3,0.1

Type RM Length L Ch R = 1 ,1942.3  ,146.3,156.3,166.3
XS GIS Cut Line= 5
     1831792.245      549737.334     1831761.863        549757.3
     1831739.294      549769.452       1831576.1      549743.411
     1831515.336       549734.73
#Sta/Elev= 25
       0   669.9     9.1  669.51    27.3  668.99    36.4  668.56    44.9  667.48
    53.4  664.88      62  660.85    71.7  656.62    81.4  654.33    91.2  654.04
   100.9  654.55   110.6  655.52   120.3  656.71     130  657.59   149.5  658.33
   168.9  658.88   207.8  660.19   217.5  661.02   227.2  663.67     236   667.3
   244.8  672.17   253.6  678.28   271.1     692   279.9  698.56   288.6  704.69
#Mann= 3 , 0 , 0
       0      .1       0    81.4    .045       0   100.9     .08       0
Bank Sta=81.4,100.9
XS Rating Curve= 0 ,0
Exp/Cntr=0.3,0.1

Type RM Length L Ch R = 1 ,1785.9  ,130.9,121.3,111.6
XS GIS Cut Line= 4
     1831789.641      549680.911      1831741.03      549647.056
     1831662.905      549589.765     1831538.773      549522.925
#Sta/Elev= 29
       0   670.8    25.4  669.98    33.8  669.18    42.3  667.42    50.8  665.15
    78.6  656.74    88.3  654.27      98  653.17   107.7  653.22   115.3  654.58
   117.4  654.96     127   657.5   136.7  659.82   146.4  661.94   156.1  663.76
   165.5  665.18   174.9  665.99   184.3   666.5   193.7  666.84   212.5  666.82
   221.9  667.04   231.3  668.06   240.7  669.32   250.1  670.18   259.5  670.66
   268.9   670.8   278.3  670.67   287.7   670.7   297.1   670.9
#Mann= 3 , 0 , 0
       0      .1       0    88.3    .045       0   115.3      .1       0
Bank Sta=88.3,115.3
XS Rating Curve= 0 ,0
Exp/Cntr=0.3,0.1

Type RM Length L Ch R = 1 ,1664.6  ,275,277.7,280.4
XS GIS Cut Line= 4
      1831861.69      549555.043     1831780.093      549524.661
     1831643.808      549488.202     1831562.211      549509.904
#Sta/Elev= 27
       0  667.62     9.7  666.31    19.4  665.25    38.7   663.6      58  662.26
    87.1  660.51   115.3  658.59   124.7   657.5  138.57  654.62   143.5  653.61
   152.9  653.12   162.3  654.42   171.7  656.25   181.1  657.24   190.5  657.34
   199.9  657.59   209.3  658.48   228.2  660.45   237.5  662.46   246.9   665.3
   256.3  667.71   265.7  669.14     275  670.03   284.4  670.76   293.8  671.26
   303.2  671.59   312.6   671.6
#Mann= 3 , 0 , 0
       0     .06       0  138.57    .045       0   162.3     .06       0
Bank Sta=138.57,162.3
XS Rating Curve= 0 ,0
Exp/Cntr=0.3,0.1

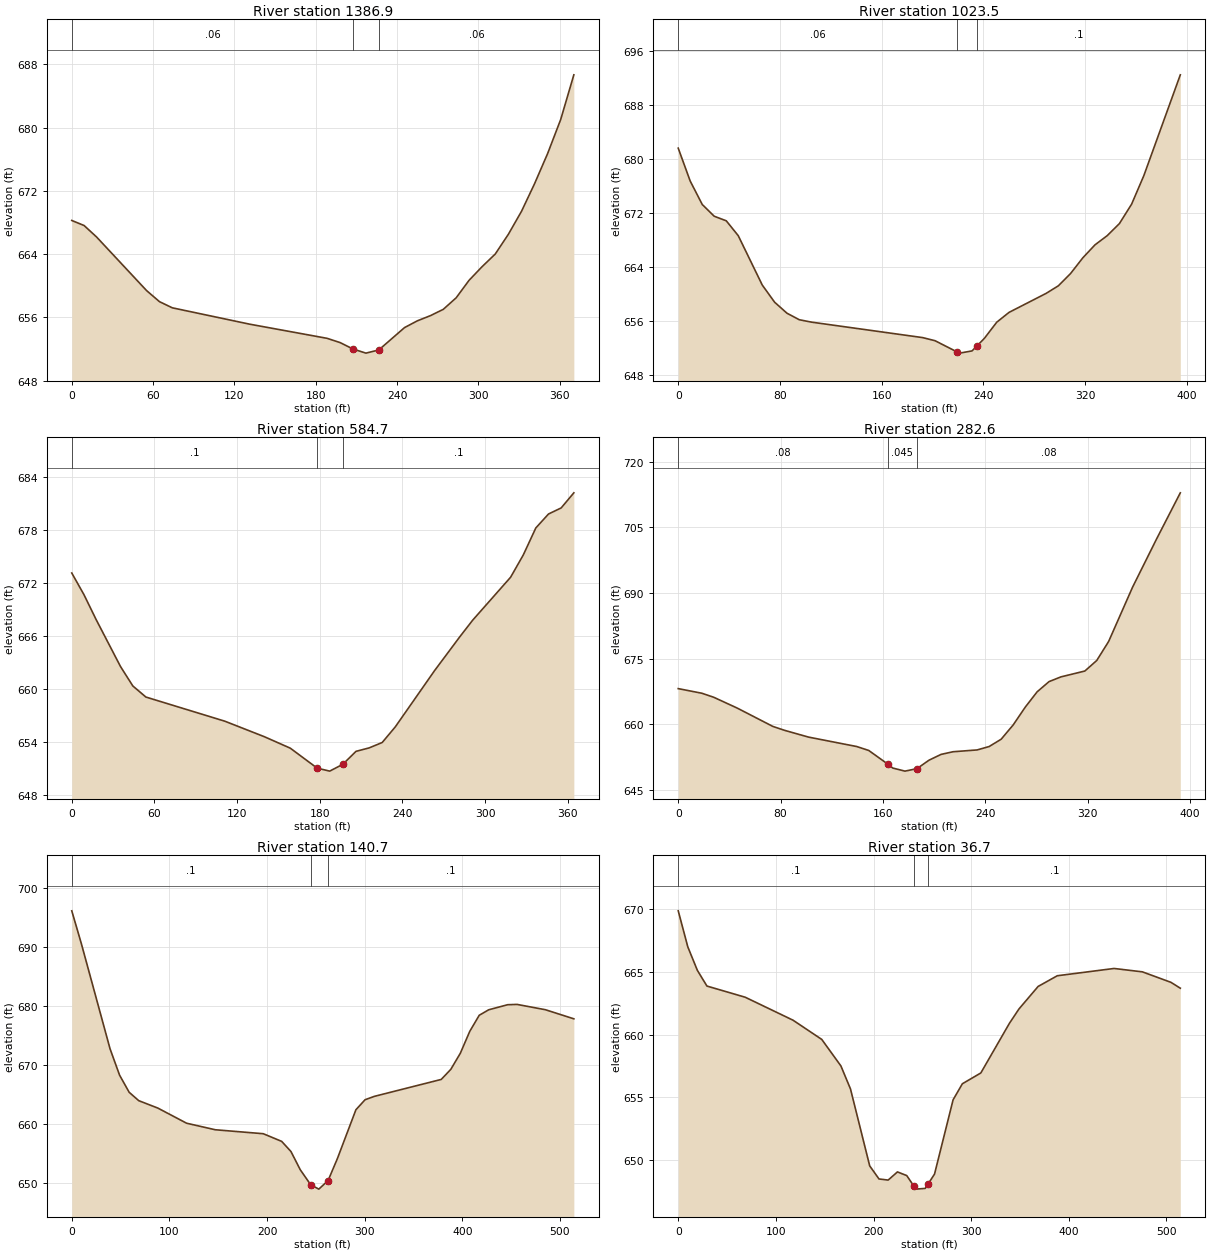
Type RM Length L Ch R = 1 ,1386.9  ,360.9,363.4,365.7
XS GIS Cut Line= 4
     1831964.988      549314.591     1831920.718      549303.306
     1831690.683      549212.161     1831621.238      549178.306
#Sta/Elev= 26
       0  668.27     9.1  667.63    18.3  666.18    55.2   659.4    64.7     658
    74.2  657.22   131.3  655.15   188.4  653.36     198  652.82   207.5  652.01
     217  651.49   226.5  651.89   245.5  654.72     255  655.58   264.6  656.23
   274.1  657.03   283.6  658.49   293.1   660.7   302.8  662.44   312.4  664.02
   322.1  666.52   331.8  669.43   341.4  672.91   351.1  676.75   360.7  681.04
   370.4  686.69
#Mann= 3 , 0 , 0
       0     .06       0   207.5    .045       0   226.5     .06       0
Bank Sta=207.5,226.5
XS Rating Curve= 0 ,0
Exp/Cntr=0.3,0.1

Type RM Length L Ch R = 1 ,1023.5  ,436.8,438.8,440.8
XS GIS Cut Line= 4
     1832118.113      549027.265     1832060.822      548994.279
     1831852.488      548890.112     1831781.308      548825.876
#Sta/Elev= 30
       0  681.58     9.4  676.71    18.9  673.23    28.3  671.49    37.8  670.81
    47.2  668.61    66.1  661.29    75.8  658.75    85.5  657.12    95.2  656.15
   104.9  655.79   192.3   653.5     202  653.04   219.6  651.35   221.4   651.2
   231.1  651.53   234.6   652.2   240.8  653.39   250.5  655.78   260.2  657.24
   289.3  660.05     299  661.18   308.6     663   318.2  665.32   327.8  667.25
   337.4  668.61     347   670.4   356.6  673.28   366.2   677.5   394.9  692.45
#Mann= 3 , 0 , 0
       0     .06       0   219.6    .045       0   234.6      .1       0
Bank Sta=219.6,234.6
XS Rating Curve= 0 ,0
Exp/Cntr=0.3,0.1

Type RM Length L Ch R = 1 ,584.7   ,298.4,302.2,305.7
XS GIS Cut Line= 4
     1832321.238      548659.209     1832281.308      548640.112
     1832095.544      548523.793     1832029.572      548447.404
#Sta/Elev= 25
       0  673.14     8.8   670.7    17.7  667.86    35.4  662.54    44.3  660.35
    53.8  659.09     111  656.36   139.6  654.61   158.6   653.3   178.1  651.04
   187.2   650.7   196.7  651.47   206.3  652.94   215.8  653.33   225.3  653.94
   234.8  655.71   263.4   662.1   281.8  665.95     291   667.8   318.5  672.66
   327.7  675.18   336.8  678.24     346  679.82   355.2  680.51   364.4  682.22
#Mann= 3 , 0 , 0
       0      .1       0   178.1    .045       0   196.7      .1       0
Bank Sta=178.1,196.7
XS Rating Curve= 0 ,0
Exp/Cntr=0.3,0.1

Type RM Length L Ch R = 1 ,282.6   ,138.6,141.9,145.1
XS GIS Cut Line= 4
     1832447.975      548468.237     1832408.044       548395.32
     1832269.155      548268.584     1832173.669      548193.931
#Sta/Elev= 30
       0  668.14    18.5  667.08    27.7  666.17    46.2  663.68    73.9  659.51
    83.1  658.61   101.9  657.06   139.5  654.91   148.9  654.01   163.7  650.91
   167.7  649.99   177.2  649.29   186.6  649.86     196  651.79   205.4  653.11
   214.8  653.72   233.6  654.13     243  654.91   252.4  656.58   261.8  659.85
   271.2   663.9   280.5  667.41   289.8  669.74   299.1  670.82   317.8  672.16
   327.1  674.57   336.4  678.92   355.1  691.32   373.7  702.24   392.4  712.87
#Mann= 3 , 0 , 0
       0     .08       0   163.7    .045       0   186.6     .08       0
Bank Sta=163.7,186.6
XS Rating Curve= 0 ,0
Exp/Cntr=0.3,0.1

Type RM Length L Ch R = 1 ,140.7   ,104,104,104
XS GIS Cut Line= 5
     1832508.738       548449.14     1832451.447       548261.64
     1832373.322      548166.154     1832326.447      548115.806
     1832300.405      547992.543
#Sta/Elev= 30
       0  696.05     9.8   690.5    39.2  672.67      49  668.19    58.8   665.3
    68.6  663.88    88.2  662.62   117.6  660.06     147  658.95   196.1  658.28
     215  656.98   224.5  655.26     234  652.18   244.7  649.63     253  648.89
   262.5  650.34     272  654.05     291  662.34   300.4  664.04   309.9  664.61
   378.4  667.48   388.2  669.19   397.9   671.9   407.6  675.62   417.3  678.35
     427  679.28   446.4  680.14   456.1  680.19   485.1  679.29   514.2  677.75
#Mann= 3 , 0 , 0
       0      .1       0   244.7    .045       0   262.5      .1       0
Bank Sta=244.7,262.5
XS Rating Curve= 0 ,0
Exp/Cntr=0.3,0.1

Type RM Length L Ch R = 1 ,36.7    ,39,36.7,34.5
XS GIS Cut Line= 5
     1832579.919      548372.751     1832522.627      548185.251
     1832444.502      548089.765     1832397.627      548039.418
     1832371.586      547916.154
#Sta/Elev= 30
       0  669.85     9.8  666.98    19.6  665.11    29.4  663.86    68.6  662.97
   117.6  661.14     147  659.61   166.6   657.5   176.4  655.67   196.1  649.54
   205.6   648.5     215  648.41   224.5  649.06     234  648.77     241  647.97
   243.5  647.69     253  647.75     256  648.11   262.5  648.89   281.5   654.8
     291  656.08   309.9  656.94   339.1  660.88   348.9  662.03   368.6  663.83
   388.2  664.68   446.4  665.26   475.4  664.99   504.5  664.16   514.2  663.69
#Mann= 3 , 0 , 0
       0      .1       0     241    .045       0     256      .1       0
Bank Sta=241,256
XS Rating Curve= 0 ,0
Exp/Cntr=0.3,0.1

Chan Stop Cuts=-1
Use User Specified Reach Order=0
Composite Channel Slope=5